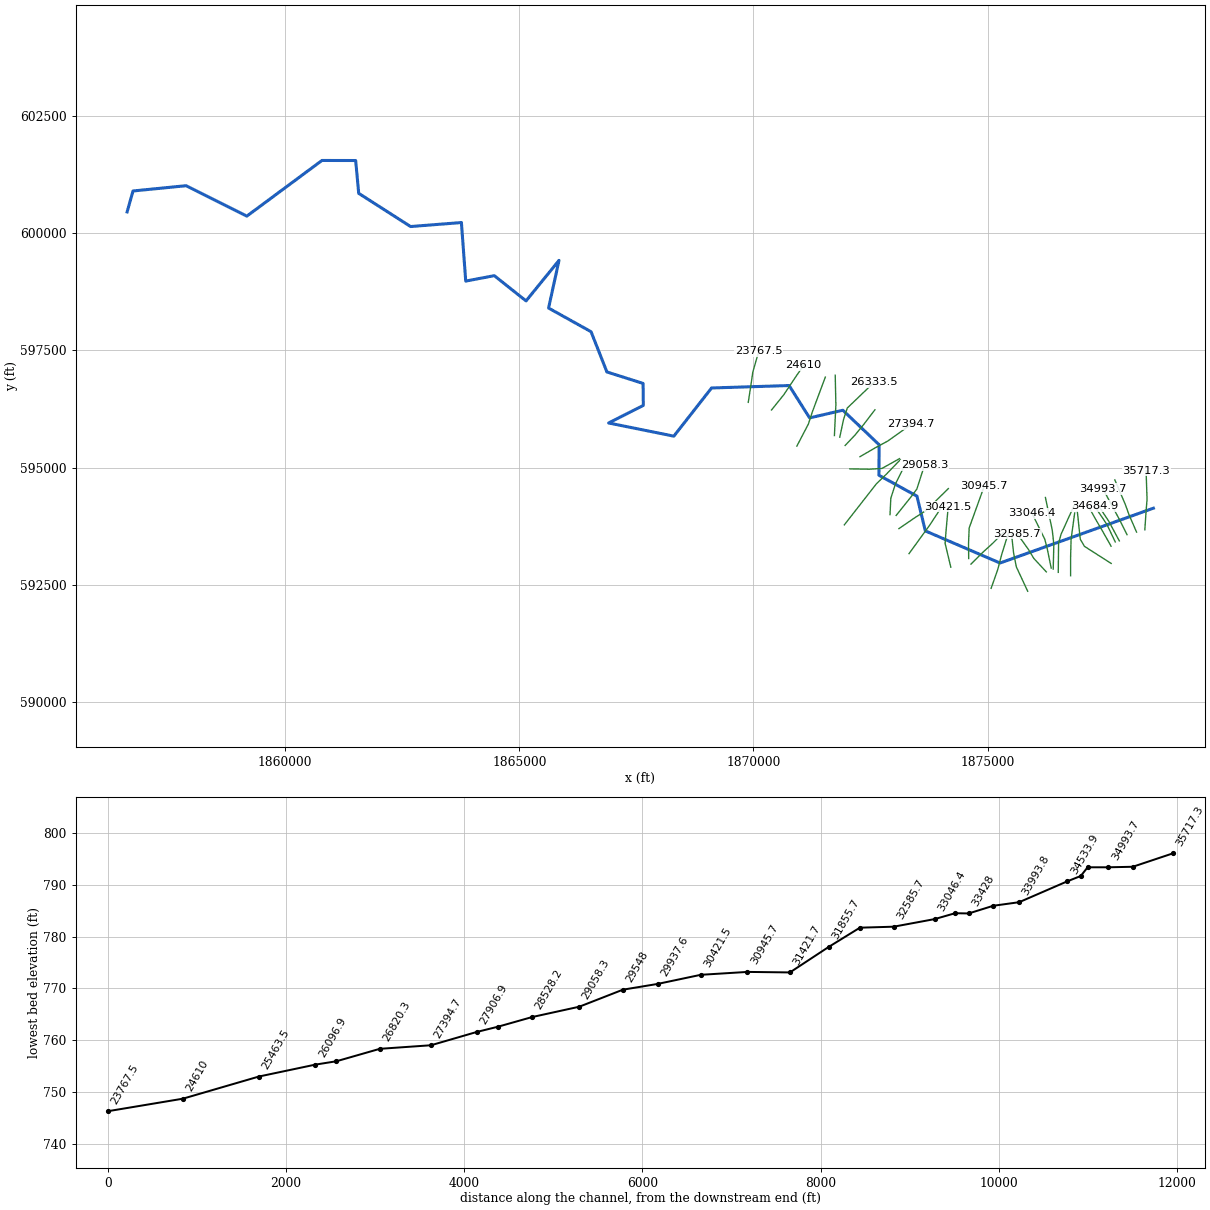
--- JohnsonCrk.prj (project) ---

Proj Title=JohnsonCrk
Current Plan=p01
Default Exp/Contr=0,0
English Units
Geom File=g01
Flow File=f01
Plan File=p01
BEGIN DESCRIPTION:
AMEC Environment & Infrastructure, 2013
Projection: NAD 1983 State Plane West Virginia South FIPS 4702 (US Feet)
Vertical Datum: NAVD 1988
END DESCRIPTION:
DSS Export Rating Curves= 0
DSS Export Rating Curve Sorted= 0
DSS Export Volume Flow Curves= 0
DXF OffsetX= 0
DXF OffsetY= 0
DXF ScaleX= 0
DXF ScaleY= 0

--- JohnsonCrk.p01 (plan) ---

Plan Title=Floodplain
Program Version=4.00
Geom File=g01
Flow File=f01
K Sum by GR=0
Std Step Tol=0.01
Critical Tol=0.01
Num of Std Step Trials=20
Max Error Tol=0.3
Flow Tol Ratio=0.001
Split Flow NTrial=30
Split Flow Tol=0.02
Split Flow Ratio=0.02
Log Output Level=0
Friction Slope Method=1
Unsteady Friction Slope Method=2
Unsteady Bridges Friction Slope Method=1
Global Log Level=0
CheckData=False
Run HTab=0
Run UNet=0
Run PostProcess=0
UNET Theta=0
UNET Theta Warmup=0
UNET ZTol=0
UNET ZSATol=0
UNET MxIter=0
UNET MaxInSteps=0
UNET DtIC=0
UNET DtMin=0
UNET MaxCRTS=0
UNET WFStab=0
UNET SFStab=0
UNET WFX=0
UNET SFX=0
UNET DSS MLevel=0
UNET DZMax Abort=0
UNET Convert EG Bridges=0
UNET Use Existing IB Tables=0
UNET Froude Limit=0
UNET Froude Power=0
Write IC File=0
Echo Input=False
Echo Output=False
Write Detailed=0

--- JohnsonCrk.f01 (steady flow) ---

Flow Title=NFF Regression Equation
Program Version=4.10
Number of Profiles= 1
Profile Names=P100yr
River Rch & RM=JohnsonCrk,Main            ,35717.3
1074.293
River Rch & RM=JohnsonCrk,Main            ,33993.8
1101.452
River Rch & RM=JohnsonCrk,Main            ,33428
1357.539
River Rch & RM=JohnsonCrk,Main            ,33046.4
1403.523
River Rch & RM=JohnsonCrk,Main            ,29937.6
1502.689
River Rch & RM=JohnsonCrk,Main            ,26333.5
1601.037
River Rch & RM=JohnsonCrk,Main            ,26096.9
1958.628
River Rch & RM=JohnsonCrk,Main            ,21594.2
2055.566
River Rch & RM=JohnsonCrk,Main            ,21185.3
2326.597
River Rch & RM=JohnsonCrk,Main            ,20245
2330.356
River Rch & RM=JohnsonCrk,Main            ,19311.5
2386.395
River Rch & RM=JohnsonCrk,Main            ,11638.4
2541.844
River Rch & RM=JohnsonCrk,Main            ,11282.4
2666.481
River Rch & RM=JohnsonCrk,Main            ,9252.1
2722.525
River Rch & RM=JohnsonCrk,Main            ,8882.6
2781.467
River Rch & RM=JohnsonCrk,Main            ,520.7
2953.123
River Rch & RM=JohnsonCrk,Main            ,125.8
2956.473
Boundary for River Rch & Prof#=JohnsonCrk,Main            , 1
Up Type= 0
Dn Type= 3
Dn Slope=0.00367
DSS Import GetInterval= 0
DSS Import GetPeak= 0
DSS Import FillOption= 0

--- JohnsonCrk.g01 (geometry) ---

Geom Title=USGS 3m DEM
Program Version=4.10

River Reach=JohnsonCrk      ,Main
Reach XY= 30
     1878543.066       594134.51     1875267.169      592964.122
     1873671.501      593649.493     1873492.134      594391.418
     1872680.445       594837.51      1872685.06      595488.317
     1871910.147      596224.822     1871199.687      596061.241
     1870762.066      596751.895     1869105.246      596699.732
      1868299.45      595671.569     1866906.598      595952.863
     1867648.159      596328.021     1867642.931      596796.932
     1866870.085      597041.779     1866531.505      597900.717
     1865623.942      598405.048     1865846.948      599422.719
     1865142.867       598557.86     1864464.956      599096.846
     1863854.566      598981.015     1863762.114      600230.258
     1862676.673      600145.114     1861568.622      600853.647
      1861503.59      601553.988     1860783.599      601555.245
     1859178.929      600367.268     1857881.579      601016.742
     1856747.513      600903.806     1856621.533      600456.635

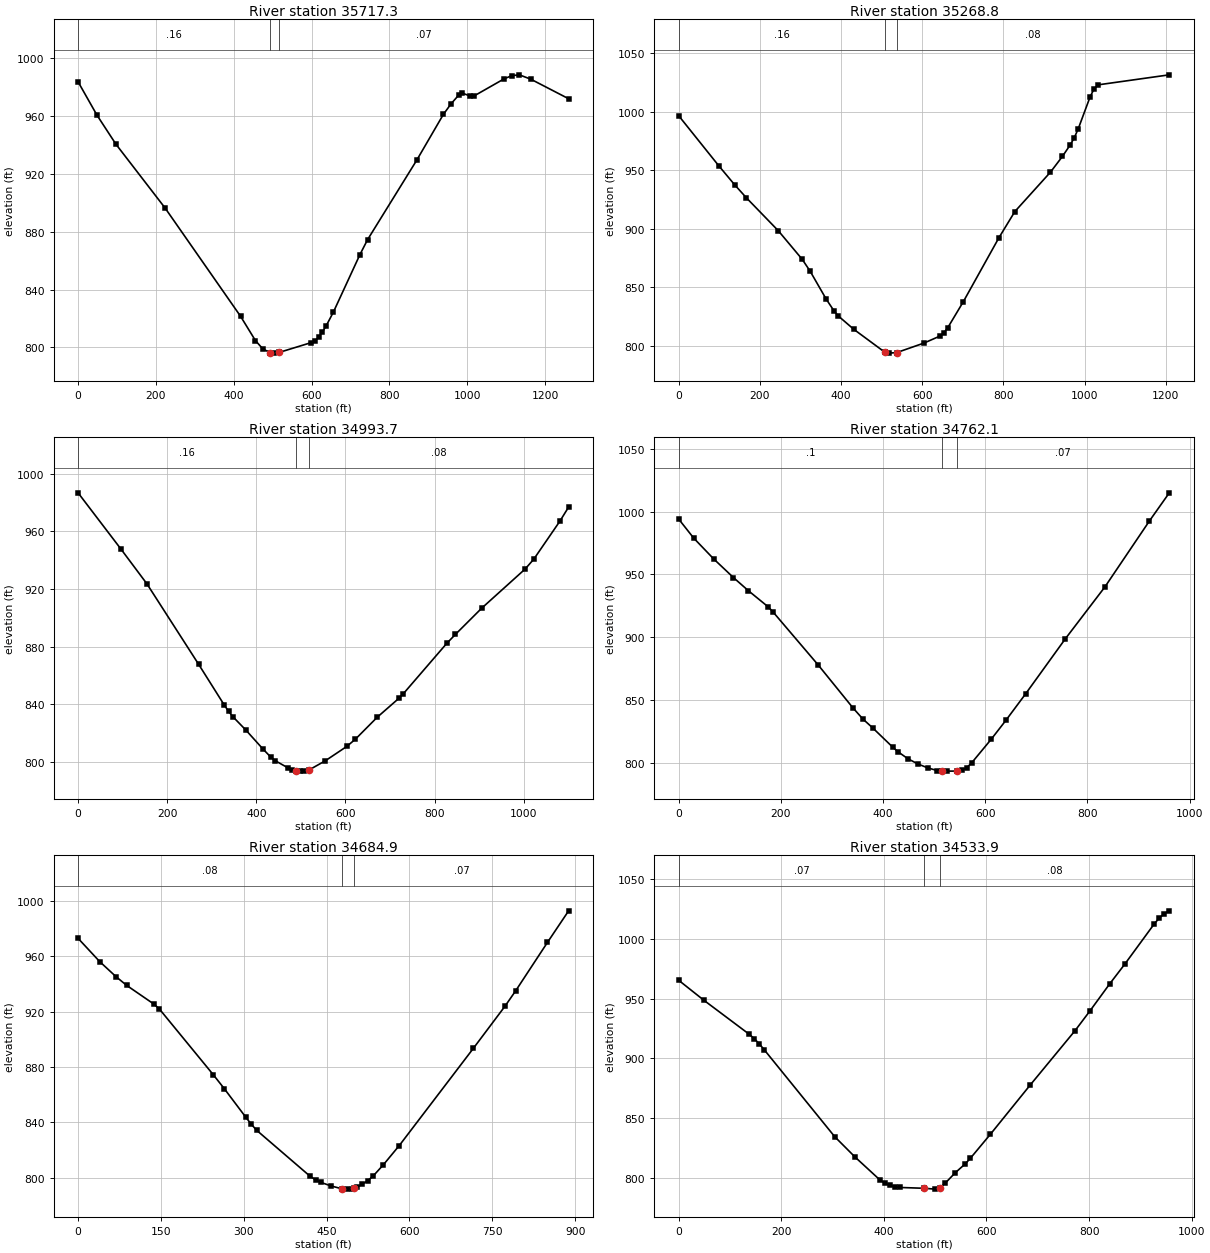
Type RM Length L Ch R = 1 ,35717.3 ,438,448.5,456.9
XS GIS Cut Line= 4
     1878359.975      593671.363     1878386.662      594068.943
     1878407.495      594325.887     1878386.662      594930.054
#Sta/Elev= 30
       0  983.41    48.6  960.37    97.2  940.36   223.5  896.32   417.6  821.53
   455.8  804.77   474.9  798.96     494  796.36   503.5  796.08   517.7  796.64
     599  803.33   608.5  804.58   618.1  806.98   627.6  810.52   637.2   814.7
   656.3  824.47   724.5  864.16     744  874.39   870.8  929.46     939  960.95
   958.5  968.15     978  974.14   987.8  975.57  1007.3  973.62    1017  973.52
    1095  985.45  1114.5  987.63    1134  988.22  1163.3  985.25  1260.8  971.71
#Mann= 3 , 0 , 0
       0     .16       0     494    .045       0   517.7     .07       0
Bank Sta=494,517.7
XS Rating Curve= 0 ,0
Exp/Cntr=0.3,0.1

Type RM Length L Ch R = 1 ,35268.8 ,272.1,275.1,278.6
XS GIS Cut Line= 4
     1878183.537       593623.63     1878022.947      593992.554
     1877944.822      594209.568     1877719.127      594739.081
#Sta/Elev= 30
       0  996.57    98.1  954.02   137.4  937.68   166.8  926.34   245.3  898.21
   304.2  873.76   323.8  863.56   363.1  839.82   382.7  829.56   392.6  825.43
   431.2   813.9   508.1  794.19   517.7   793.5   536.9  793.95   604.2  802.11
   642.8  807.98   652.5   810.6   662.3  814.97   701.3  837.62   789.1   892.4
   828.1  914.65   915.9  948.39   945.2  961.78   964.7  971.78   974.5  977.83
   984.2  985.39  1013.5  1012.8  1023.2 1019.56    1033 1023.04  1208.6 1031.62
#Mann= 3 , 0 , 0
       0     .16       0   508.1    .045       0   536.9     .08       0
Bank Sta=508.1,536.9
XS Rating Curve= 0 ,0
Exp/Cntr=0.3,0.1

Type RM Length L Ch R = 1 ,34993.7 ,230.1,231.6,233.3
XS GIS Cut Line= 4
     1877979.544      593569.377     1877805.933      593914.429
     1877716.957      594079.359     1877467.391      594543.769
#Sta/Elev= 30
       0  986.79    96.6  947.55   154.5  923.55   270.4  867.71   328.3  839.22
     338  834.84   347.6  831.16   376.6  821.92   414.4  808.94   433.1  802.95
   442.5  800.64   470.6  795.75     480  794.19   489.3  793.44   498.7   793.4
   508.1  793.42   517.4  794.06   554.9  800.59     603  810.56   622.5  815.63
   671.3  830.83   720.1  844.03   729.9  847.16   827.5  882.21     847  888.46
   905.6  906.56  1003.2  933.81  1022.8  940.72  1081.4  967.15  1100.9   976.9
#Mann= 3 , 0 , 0
       0     .16       0   489.3    .045       0   517.4     .08       0
Bank Sta=489.3,517.4
XS Rating Curve= 0 ,0
Exp/Cntr=0.3,0.1

Type RM Length L Ch R = 1 ,34762.1 ,77.5,77.2,77
XS GIS Cut Line= 4
     1877814.614      593436.998     1877588.919      593858.005
     1877493.433      594001.234     1877324.162      594261.651
#Sta/Elev= 30
       0  994.01    29.2  978.96    68.2  962.43   107.2  947.46   136.5  936.98
   175.5  924.05   185.2  919.83     273  877.91   341.2  843.68   360.7  834.81
   380.2  827.64   419.2  812.37   428.9  808.93   448.4  803.31   467.9  799.17
   487.2  796.02   506.4   793.8   515.9  793.49   525.5   793.4   544.6  793.45
   554.2  794.05   563.8  796.16   573.3  799.89   611.6  818.71   640.3  833.74
     679  854.87   756.6  898.61   834.2  939.97   921.6  992.64   960.4 1014.96
#Mann= 3 , 0 , 0
       0      .1       0   515.9    .045       0   544.6     .07       0
Bank Sta=515.9,544.6
XS Rating Curve= 0 ,0
Exp/Cntr=0.3,0.1

Type RM Length L Ch R = 1 ,34684.9 ,151.9,151.1,150.2
XS GIS Cut Line= 4
     1877727.808      593415.297     1877558.537      593769.029
     1877482.582      593888.387      1877282.93      594181.356
#Sta/Elev= 30
       0  972.98    39.2  956.16    68.6  945.31    88.2  938.91   137.2  925.48
   147.1  921.97   245.1  874.26   264.7  864.35   303.9  843.56   313.7   838.6
   323.5  834.19   420.4  800.92   429.9  798.48   439.3  796.63   458.2     794
     477  792.05   486.5  791.72   495.9  791.94   499.8  792.46   505.3  793.22
   514.8  795.32   524.2  797.81   533.6  800.91   552.8  809.33   581.5  823.18
   715.7  893.47   773.2  924.04   792.3  935.05   849.8     970   888.2  992.86
#Mann= 3 , 0 , 0
       0     .08       0     477    .045       0   499.8     .07       0
Bank Sta=477,499.8
XS Rating Curve= 0 ,0
Exp/Cntr=0.3,0.1

Type RM Length L Ch R = 1 ,34533.9 ,540.3,540.1,540.5
XS GIS Cut Line= 4
     1877638.832      593324.151     1877430.499      593690.904
     1877311.141      593892.727     1877165.742      594155.314
#Sta/Elev= 30
       0  965.19      49  948.54   137.3  920.15   147.1  916.51     157   912.1
   166.8  907.11   304.1  834.52   343.3  817.68   392.4   798.3   402.2  795.56
     412  793.73   421.8  792.78   431.6  792.07   478.6  791.39     500  790.69
   509.7  791.82   519.5  795.66     539  804.35   558.6  811.82   568.3  816.34
   607.4  836.44   685.3  877.74   772.5  923.06   801.5  939.51   840.2  962.25
   869.3  978.53   927.4 1012.56   937.1 1017.36   946.7 1020.91   956.4 1023.28
#Mann= 3 , 0 , 0
       0     .07       0   478.6    .045       0   509.7     .08       0
Bank Sta=478.6,509.7
XS Rating Curve= 0 ,0
Exp/Cntr=0.3,0.1

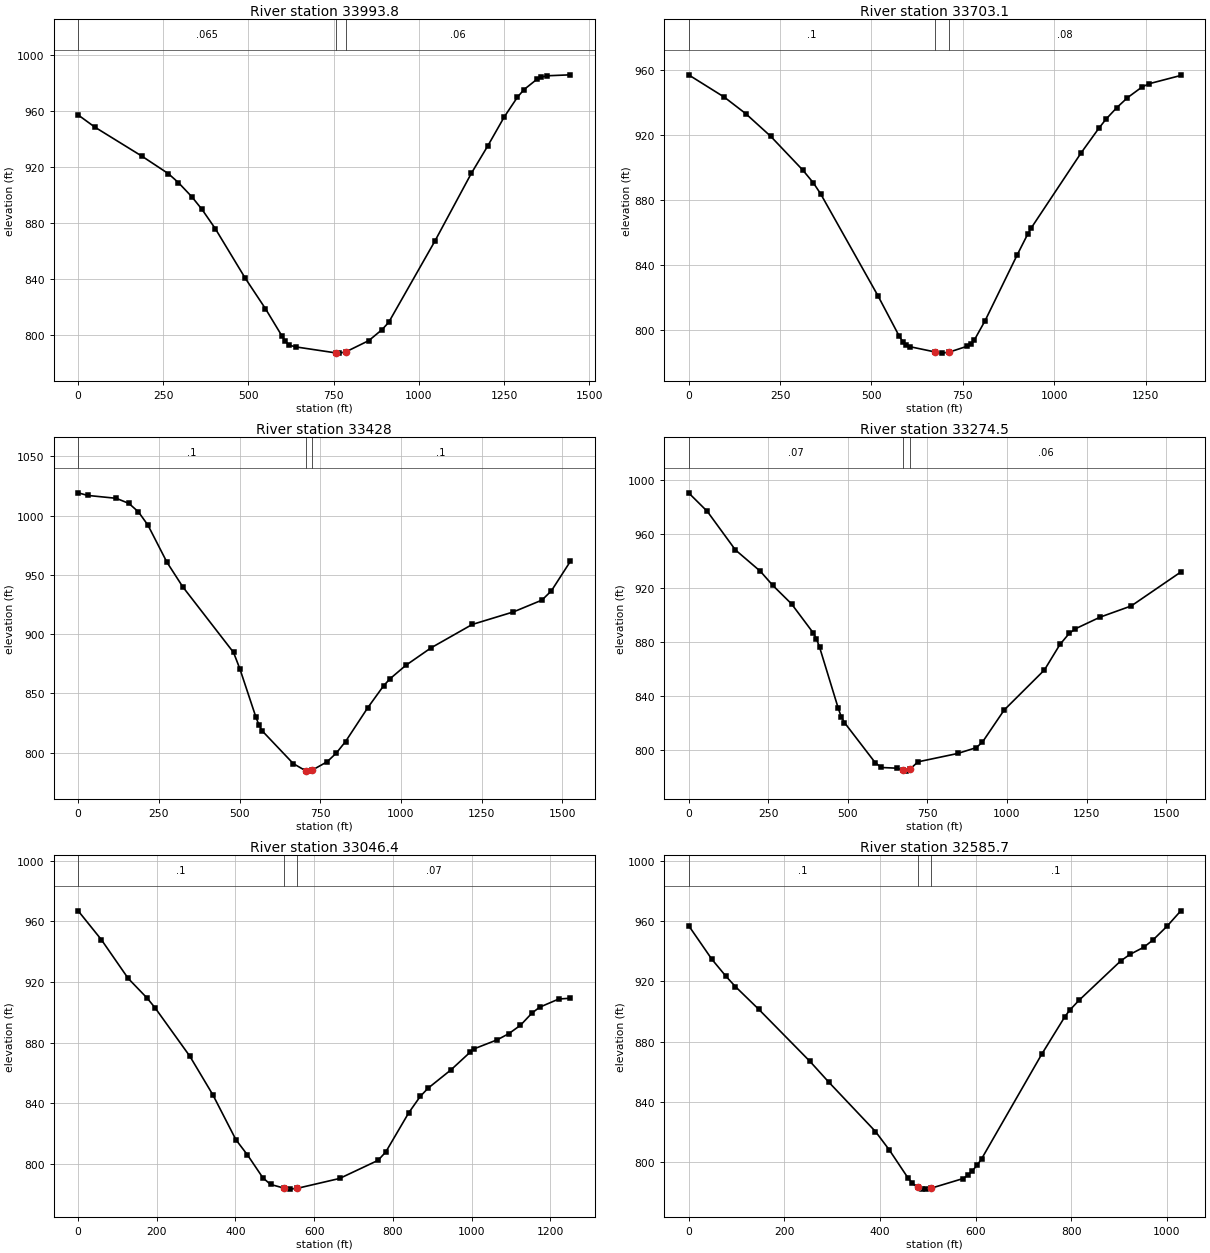
Type RM Length L Ch R = 1 ,33993.8 ,303.3,290.7,277.3
XS GIS Cut Line= 4
     1877641.002      592955.227     1877070.256      593319.811
      1876981.28       593471.72     1876918.346      594059.828
#Sta/Elev= 30
       0  957.24    49.1  948.51   186.5  927.82     265  915.17   294.5  908.74
   333.7  898.64   363.2   889.7   402.4  875.87   490.8   840.2   549.7  818.52
   598.7  798.75   608.6  795.07   618.4  792.47     638  791.15   756.2  786.83
   765.3  786.66   784.8  787.45   853.3  795.65   892.1  803.51   911.5  808.69
  1047.2  866.92  1153.9  915.33  1202.4  935.08  1250.8  955.86  1289.6  970.03
    1309  975.47  1347.8  983.01  1357.5   984.3  1376.9   985.3  1444.8  985.98
#Mann= 3 , 0 , 0
       0    .065       0   756.2    .045       0   784.8     .06       0
Bank Sta=756.2,784.8
XS Rating Curve= 0 ,0
Exp/Cntr=0.3,0.1

Type RM Length L Ch R = 1 ,33703.1 ,280.1,275.1,269.5
XS GIS Cut Line= 4
     1876774.683      592691.772     1876774.683      593101.495
       1876785.1      593473.022     1876861.489       594032.05
#Sta/Elev= 30
       0  957.02    97.6   943.3   156.1  933.18   224.4  919.25   312.2  898.48
   341.4  890.52     361  883.86   517.3  821.37     576  796.33   585.8  792.95
   595.6  790.88   605.3  789.91   674.2  786.67   693.4  785.97   712.9  786.62
   761.8  790.22   771.6  791.56   781.4  794.12   810.6  805.92   898.1  846.25
   927.3  859.22     937  862.99  1073.2   909.1  1121.9  924.29  1141.3  929.82
  1170.5  936.82  1199.7  942.95  1238.6  949.37  1258.1   951.5  1345.6  956.63
#Mann= 3 , 0 , 0
       0      .1       0   674.2    .045       0   712.9     .08       0
Bank Sta=674.2,712.9
XS Rating Curve= 0 ,0
Exp/Cntr=0.3,0.1

Type RM Length L Ch R = 1 ,33428   ,144.9,153.5,161.9
XS GIS Cut Line= 4
     1876510.794      592764.689     1876517.739      593383.613
     1876569.822      593576.321     1876861.489       594219.55
#Sta/Elev= 30
       0  1019.2    29.5 1017.01   117.9 1014.58   157.2 1010.27   186.7 1003.15
   216.2  991.94   275.1  960.64   324.2  939.88   481.4  884.58   501.1  870.67
   550.2  830.39     560  823.48   569.8  818.54   666.5   790.8   704.5  784.86
     714  784.49   723.5   785.1   771.1  792.34   799.6  799.67   828.4  809.46
   897.1  837.94   946.1  856.42   965.7  862.28  1014.8  873.64  1093.2  888.46
  1220.8  908.18  1348.3  918.76  1436.6   928.7    1466  936.52  1524.8   961.4
#Mann= 3 , 0 , 0
       0      .1       0   704.5    .045       0   723.5      .1       0
Bank Sta=704.5,723.5
XS Rating Curve= 0 ,0
Exp/Cntr=0.3,0.1

Type RM Length L Ch R = 1 ,33274.5 ,224.9,228.1,231.5
XS GIS Cut Line= 4
     1876403.155      592834.133     1876416.176      593362.779
     1876382.322      593667.467     1876236.489      594362.779
#Sta/Elev= 30
       0  990.85    58.8  977.07   146.9  948.55   225.2  932.73   264.4  922.23
   323.2  908.53   391.7  886.93   401.5   882.6   411.3  876.44     470  831.12
   479.8  824.58   489.6  820.48   586.3  790.73   605.4  787.22   653.4  786.72
   672.5  785.18   682.1  784.53   696.7  786.28   720.4  791.42   845.1  797.61
   903.5  801.94     923   806.1   991.1  829.84  1117.6  859.56  1166.3  878.46
  1195.5  886.66  1214.9  890.07  1292.8  898.73  1390.1  906.98  1545.8  932.14
#Mann= 3 , 0 , 0
       0     .07       0   672.5    .045       0   696.7     .06       0
Bank Sta=672.5,696.7
XS Rating Curve= 0 ,0
Exp/Cntr=0.3,0.1

Type RM Length L Ch R = 1 ,33046.4 ,453.4,460.7,462
XS GIS Cut Line= 4
     1876359.752      592855.748     1876273.815      593277.623
     1876221.732       593475.54     1875948.294      594027.623
#Sta/Elev= 30
       0  967.01    58.7  948.08   127.2  922.42   176.1  909.22   195.7  902.96
   283.8  871.14   342.5   845.6   401.2  815.94   430.5  805.95   469.5  790.92
     489   786.5   522.5  784.14   537.5   783.4   557.2  783.94   664.5  790.42
   762.3  802.38   781.9  807.86   840.6  833.85   869.9  844.64   889.4  849.95
   948.1  862.16     997  873.86  1006.8  875.98  1065.5  881.93  1094.8  885.97
  1124.2  891.45  1153.5   899.5    1173   903.4  1221.9  908.83  1251.3  909.34
#Mann= 3 , 0 , 0
       0      .1       0   522.5    .045       0   557.2     .07       0
Bank Sta=522.5,557.2
XS Rating Curve= 0 ,0
Exp/Cntr=0.3,0.1

Type RM Length L Ch R = 1 ,32585.7 ,386.7,378.7,374
XS GIS Cut Line= 4
     1876255.586      592775.019     1875989.961      593061.477
     1875870.169      593259.394      1875633.19      593590.123
#Sta/Elev= 30
       0  957.21    48.8  934.71    78.1  923.48    97.7  916.65   146.5  901.56
   253.9  866.81     293  853.09   390.7  820.23   419.6  807.97   458.1  789.62
   467.8  785.78   479.1  783.03     487  782.03   496.7  781.93   506.3  782.48
   573.8  788.96   583.4  791.07   593.1  794.12   602.7  797.66   612.4  802.04
   738.2  871.66   786.7  896.66   796.4  900.82   815.8  907.39   902.9  933.57
   922.3  937.96   951.4  942.76   970.8  947.61   999.8  956.64  1028.9  966.99
#Mann= 3 , 0 , 0
       0      .1       0   479.1    .045       0   506.3      .1       0
Bank Sta=479.1,506.3
XS Rating Curve= 0 ,0
Exp/Cntr=0.3,0.1

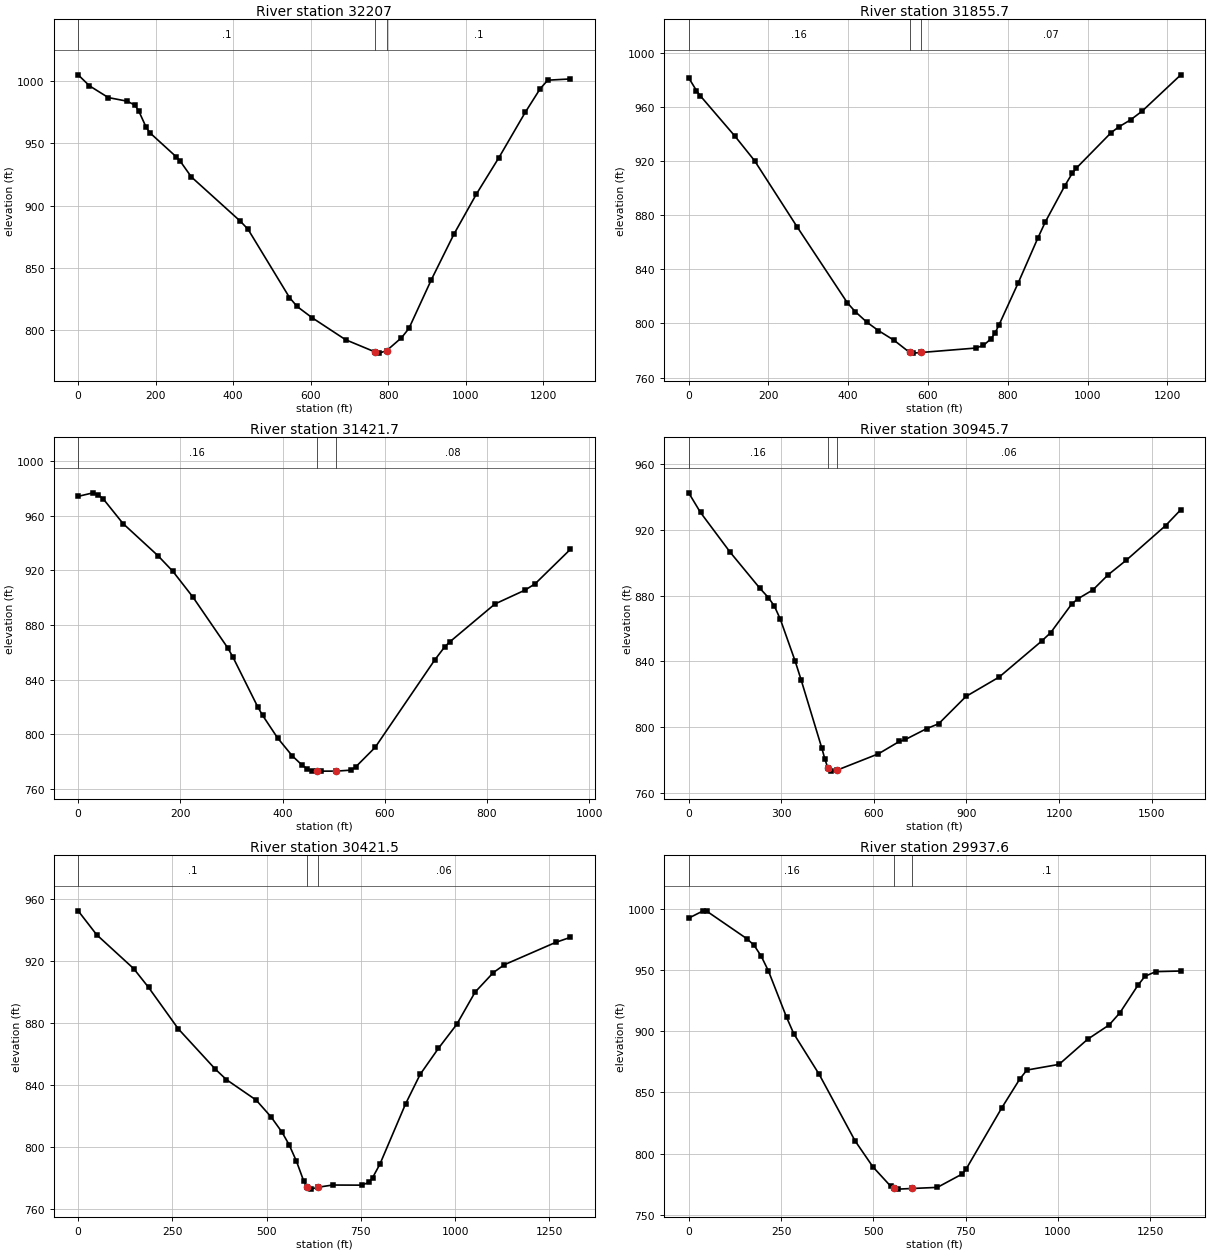
Type RM Length L Ch R = 1 ,32207   ,361,351.4,340.9
XS GIS Cut Line= 4
     1875858.016      592361.824     1875614.961      592882.658
     1875555.933      593184.741     1875514.266      593570.158
#Sta/Elev= 30
       0 1004.76    29.2  995.95    77.9  986.52   126.6  983.63   146.1  980.53
   155.9  976.13   175.4  962.82   185.1  958.33   253.3  939.03     263  935.77
   292.2  922.93   418.9  887.38   438.4  881.02   545.5   826.3     565  819.16
   603.6  810.17   690.2   792.5   767.1  782.58   776.8  781.74     796  783.66
   834.5  794.03   853.7  801.48   911.6  840.54   969.8     877  1027.9  909.18
  1086.1  938.44  1153.9  974.63  1192.7   993.7  1212.1 1000.46  1270.2 1001.46
#Mann= 3 , 0 , 0
       0      .1       0   767.1    .045       0     796      .1       0
Bank Sta=767.1,796
XS Rating Curve= 0 ,0
Exp/Cntr=0.3,0.1

Type RM Length L Ch R = 1 ,31855.7 ,446.6,434,421.1
XS GIS Cut Line= 4
     1875076.766      592424.324     1875219.127      592827.102
     1875305.933      593156.963     1875444.822      593601.408
#Sta/Elev= 30
       0  981.36    19.4  971.95    29.1  968.07   116.5  938.07     165  920.21
   271.8   871.3   398.1  815.06   417.5  808.69   446.7  800.86   475.9  794.62
   514.9   787.5   553.9  778.52   563.6  778.01   583.1  778.49   719.6  781.76
     739  783.71   758.5  788.74   768.3     793     778   798.8   826.5  830.08
     875  862.72   894.4  875.05   942.9  901.55   962.3  911.12     972  914.67
  1059.3   940.9  1078.7  945.16  1107.8  950.29  1136.9  956.74  1233.9  983.57
#Mann= 3 , 0 , 0
       0     .16       0   553.9    .045       0   583.1     .07       0
Bank Sta=553.9,583.1
XS Rating Curve= 0 ,0
Exp/Cntr=0.3,0.1

Type RM Length L Ch R = 1 ,31421.7 ,458.2,476,493.5
XS GIS Cut Line= 4
     1874646.211      592941.686     1874917.044      593209.047
     1875101.072      593375.713     1875337.183      593611.824
#Sta/Elev= 30
       0  974.23    29.3  976.81      39   975.4    48.8   972.5    87.8  954.32
   156.1  930.82   185.4  919.31   224.4  900.58   292.8  863.22   302.5   856.8
   351.3  820.18     361  813.85   390.1  797.44   418.8  784.32   437.9  777.58
   447.4  774.89     457  773.42   466.5  773.13   475.9   773.1   504.7   773.1
   533.4  773.82   542.9  776.14   581.1  790.49   697.6  854.45   717.2   864.1
   727.1  867.71   815.4  895.44   874.4  905.62     894  910.21   962.8  935.37
#Mann= 3 , 0 , 0
       0     .16       0   466.5    .045       0   504.7     .08       0
Bank Sta=466.5,504.7
XS Rating Curve= 0 ,0
Exp/Cntr=0.3,0.1

Type RM Length L Ch R = 1 ,30945.7 ,525.2,524.3,522.8
XS GIS Cut Line= 4
       1874597.6      593059.741     1874594.127      593375.713
     1874608.016      593712.519     1874927.461      594597.936
#Sta/Elev= 30
       0  942.47    38.3  930.51   134.1   906.4   229.8   884.6   258.5  878.67
   277.7  873.55   296.8  865.62   344.9  840.11   364.2  828.73   431.6  787.02
   441.2  780.54   450.8  775.12   460.5   773.2   479.7  773.72   614.6  783.72
   682.5  791.25   702.1  792.44   770.7  799.02     810  802.03   898.2   818.6
  1006.1  830.44  1143.3  852.26  1172.8  857.42  1241.4  874.96    1261  878.01
    1310  883.49    1359  892.63  1417.9  901.51  1545.3  922.58  1594.4  932.21
#Mann= 3 , 0 , 0
       0     .16       0   450.8    .045       0   479.7     .06       0
Bank Sta=450.8,479.7
XS Rating Curve= 0 ,0
Exp/Cntr=0.3,0.1

Type RM Length L Ch R = 1 ,30421.5 ,496.2,483.8,470.2
XS GIS Cut Line= 4
     1874215.655      592875.713     1874094.127      593382.658
     1874111.489      593622.241       1874160.1      594163.908
#Sta/Elev= 30
       0  952.63    49.2  937.15   147.5   915.2   186.9  903.07   265.6  876.31
   363.9  850.23   393.4  843.44   472.1  830.25   511.5  819.43   540.5  809.57
   559.7  801.32     579  790.74   598.2  777.96   607.8  773.83   617.4  772.64
   636.6  773.87     675  775.29   751.9  775.21   771.2  776.99   780.9  779.98
   800.4  788.76   868.4  827.69   907.2  846.83   955.8  863.73  1004.3  879.21
  1052.9  900.03  1101.4   912.7  1130.6  917.77  1266.5   932.2  1305.4  935.45
#Mann= 3 , 0 , 0
       0      .1       0   607.8    .045       0   636.6     .06       0
Bank Sta=607.8,636.6
XS Rating Curve= 0 ,0
Exp/Cntr=0.3,0.1

Type RM Length L Ch R = 1 ,29937.6 ,398.1,389.6,381.3
XS GIS Cut Line= 4
     1873323.294      593163.908     1873542.044      593465.991
     1873764.266      593771.547     1874083.711      594257.658
#Sta/Elev= 30
       0  992.59    39.3  998.57    49.1  998.24     157  975.85   176.7  970.55
   196.3  961.51   215.9   949.4     265  911.47   284.6  897.98   353.3  864.79
   450.5  810.38   498.9  789.06   547.4   773.1     557   771.4   566.7  770.88
   604.9  771.41   673.3   772.3   741.1  783.34   750.8   787.1   847.7  837.36
   896.2  860.82   915.6  868.29  1002.8  872.94  1080.4  893.54  1138.6  905.24
  1167.7   915.2  1216.1  937.54  1235.5  945.03  1264.6  948.81  1332.5  949.33
#Mann= 3 , 0 , 0
       0     .16       0     557    .045       0   604.9      .1       0
Bank Sta=557,604.9
XS Rating Curve= 0 ,0
Exp/Cntr=0.3,0.1

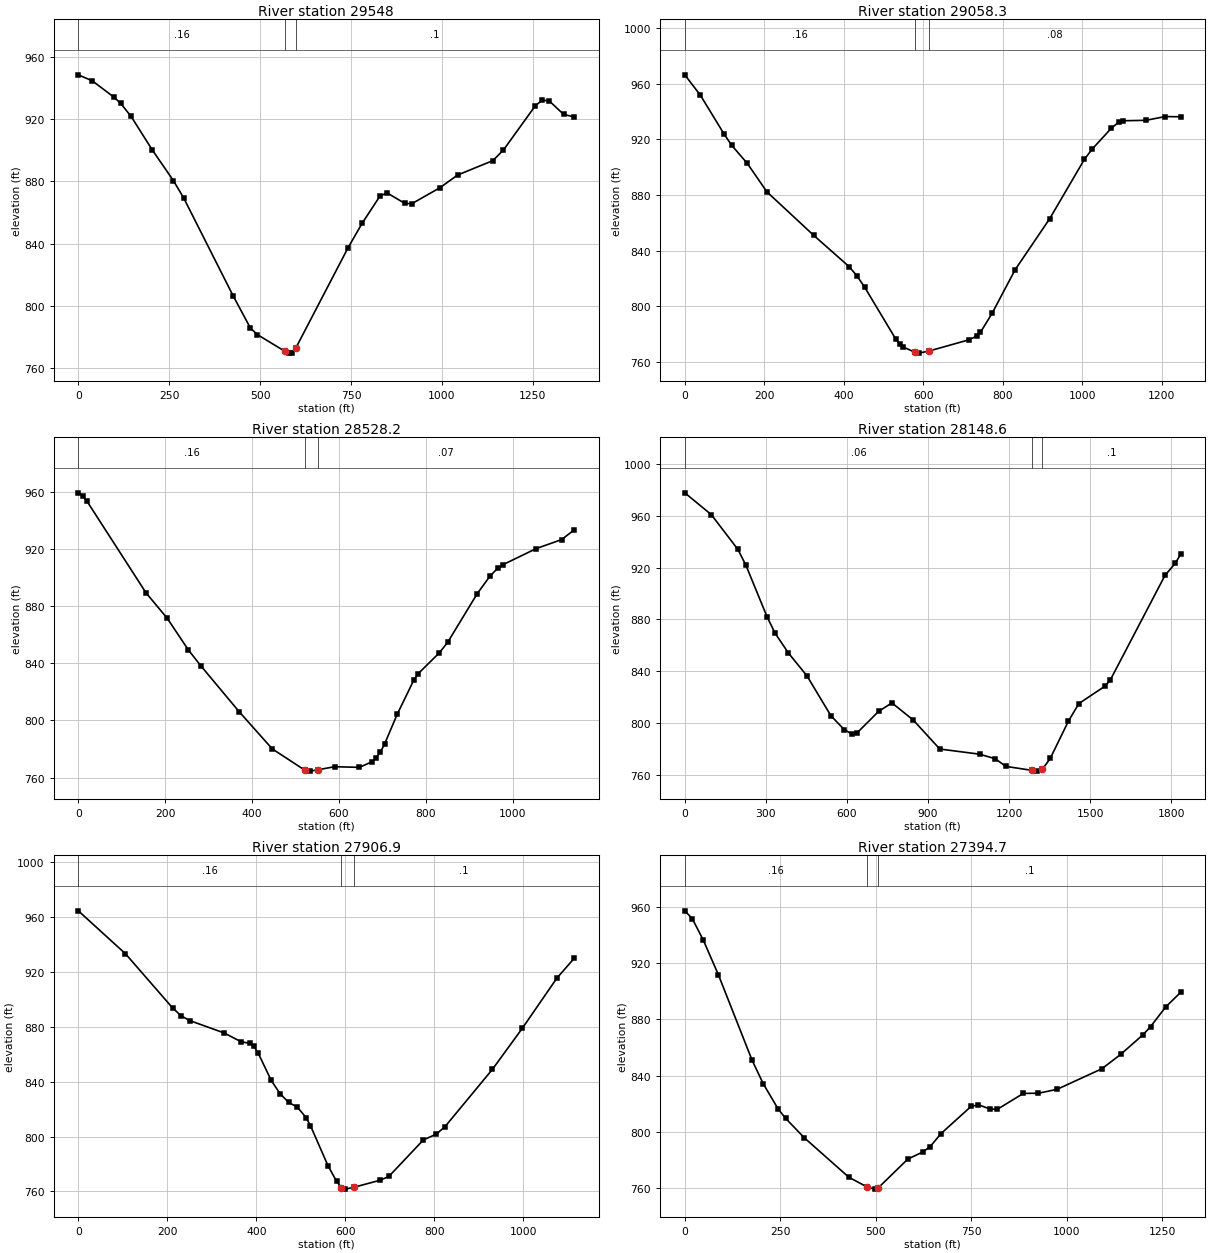
Type RM Length L Ch R = 1 ,29548   ,481.4,489.7,497.5
XS GIS Cut Line= 4
     1873108.016       593698.63     1873427.461       593917.38
     1873684.405      594084.047     1874163.572      594552.797
#Sta/Elev= 30
       0  948.36    38.7  944.47    96.8  934.22   116.2  930.13   145.2  921.63
   203.3   900.2   261.3  880.54   290.4  869.07   425.4  806.72   473.3  785.86
   492.4  781.67   567.2  771.09   578.6  769.77   588.2  770.01   597.7   772.8
     742  837.45   780.9  853.18   829.4  870.45   848.9  872.64   897.4  865.94
   916.9   865.6   994.6  875.91  1043.2  884.05  1140.3  893.32  1169.4  900.15
  1256.9  928.49  1276.3  932.19  1295.7  931.53  1334.6  923.02  1363.8   921.3
#Mann= 3 , 0 , 0
       0     .16       0   567.2    .045       0   597.7      .1       0
Bank Sta=567.2,597.7
XS Rating Curve= 0 ,0
Exp/Cntr=0.3,0.1

Type RM Length L Ch R = 1 ,29058.3 ,522.3,530.1,537.2
XS GIS Cut Line= 4
     1873048.989       593979.88     1873368.433      594379.186
     1873489.961       594542.38     1873653.155      595049.324
#Sta/Elev= 30
       0  966.47    39.3  951.77    98.3  924.15     118   915.8   157.3  902.81
   206.5   882.4   324.5  851.06     413  828.73   432.7  822.16   452.4   813.9
   530.7  776.58   540.4  773.13   550.1  770.78   579.2  767.07   588.9  766.48
   614.1  767.97   714.8  776.05   734.2  778.68   743.9  781.44   772.9  794.98
     831  826.38   918.2  863.16  1005.3  905.72  1024.7  913.03  1073.1  928.12
  1092.5  932.63  1102.2  933.46  1160.2  933.79  1208.7  936.48  1247.4  936.32
#Mann= 3 , 0 , 0
       0     .16       0   579.2    .045       0   614.1     .08       0
Bank Sta=579.2,614.1
XS Rating Curve= 0 ,0
Exp/Cntr=0.3,0.1

Type RM Length L Ch R = 1 ,28528.2 ,391,379.7,368.8
XS GIS Cut Line= 4
     1872917.044      593997.241     1872934.405      594347.936
       1873035.1      594656.963     1873243.433       595073.63
#Sta/Elev= 30
       0   959.2     9.8  957.13    19.5  953.52   156.1  889.13   204.8   871.4
   253.6  849.21   282.8  837.93   370.2  806.14   446.7  780.03   522.4  765.01
   532.8  764.48   551.9  765.41   590.1  767.57   647.5  767.12   676.1  770.99
   685.8  773.76   695.6  777.74   705.3  783.39   734.4  804.23   773.2  828.49
   782.9  832.72   831.4  847.23   850.8  854.67   918.8  888.68   947.9  900.83
   967.3   906.9     977  908.78  1054.6  920.19  1112.9  926.45    1142  933.24
#Mann= 3 , 0 , 0
       0     .16       0   522.4    .045       0   551.9     .07       0
Bank Sta=522.4,551.9
XS Rating Curve= 0 ,0
Exp/Cntr=0.3,0.1

Type RM Length L Ch R = 1 ,28148.6 ,258.2,241.7,225.1
XS GIS Cut Line= 4
      1871941.35      593778.491     1872625.377      594653.491
       1872847.6      594868.769     1873135.794       595167.38
#Sta/Elev= 30
       0  977.74    98.3  960.85   196.6  933.97   226.1   921.8   304.7  881.78
   334.2  869.26   383.3  853.96   452.1  836.28   540.6  805.48   589.7   794.8
   619.2  791.19   638.9  792.48   717.5  808.83   766.6  815.37   845.3  802.16
   943.6  779.71    1091  775.73  1149.3  772.17    1188  766.29  1284.8  763.23
    1304  762.63  1323.4  764.05  1352.4   772.4    1420   801.4  1458.6  814.88
  1555.2  828.32  1574.5  832.98  1777.1  913.89  1815.7   923.4    1835   930.3
#Mann= 3 , 0 , 0
       0     .06       0  1284.8    .045       0  1323.4      .1       0
Bank Sta=1284.8,1323.4
XS Rating Curve= 0 ,0
Exp/Cntr=0.3,0.1

Type RM Length L Ch R = 1 ,27906.9 ,502.4,512.2,521.9
XS GIS Cut Line= 4
     1872059.405      594972.936     1872483.016      594965.991
     1872746.905      594983.352     1873118.433      595191.686
#Sta/Elev= 30
       0  964.67   105.9  933.35   211.8  893.82   231.1  888.02   250.4  884.58
   327.4  875.58   365.9  869.11   385.2  868.01   394.8  865.75   404.4  860.65
   433.5  840.87     453  831.37   472.6  824.83   492.2  821.45   511.8  813.75
   521.6  807.91   560.8  778.81   580.4  767.22   591.1  762.77     600   761.6
   619.6  762.98   678.3  768.12   697.8  770.87   775.2  797.49   804.3  801.73
   823.7  807.11   930.2   848.9   997.9  879.09  1075.4  915.61  1114.1  929.99
#Mann= 3 , 0 , 0
       0     .16       0   591.1    .045       0   619.6      .1       0
Bank Sta=591.1,619.6
XS Rating Curve= 0 ,0
Exp/Cntr=0.3,0.1

Type RM Length L Ch R = 1 ,27394.7 ,565.4,574.4,582.7
XS GIS Cut Line= 4
     1872274.683      595233.352     1872604.544      595424.324
     1872868.433      595566.686     1873371.905      595924.324
#Sta/Elev= 30
       0  957.33    19.6  951.76    48.9   936.2      88  911.75   175.9   851.1
   205.2  834.24   244.3  816.21   263.9  809.52   312.7   795.7   429.5  767.54
   476.7  760.68   497.2  759.04   506.9  760.02   584.3  780.48     623  785.46
   642.3  789.24   671.3  798.67   749.6  817.94   769.2  819.13   798.6  816.19
   818.2  815.85   886.8  827.26   926.1  827.35   975.1  830.16  1092.7  844.84
  1141.7  855.07  1200.5  869.14  1220.1   874.9  1259.4  888.81  1298.6  899.22
#Mann= 3 , 0 , 0
       0     .16       0   476.7    .045       0   506.9      .1       0
Bank Sta=476.7,506.9
XS Rating Curve= 0 ,0
Exp/Cntr=0.3,0.1

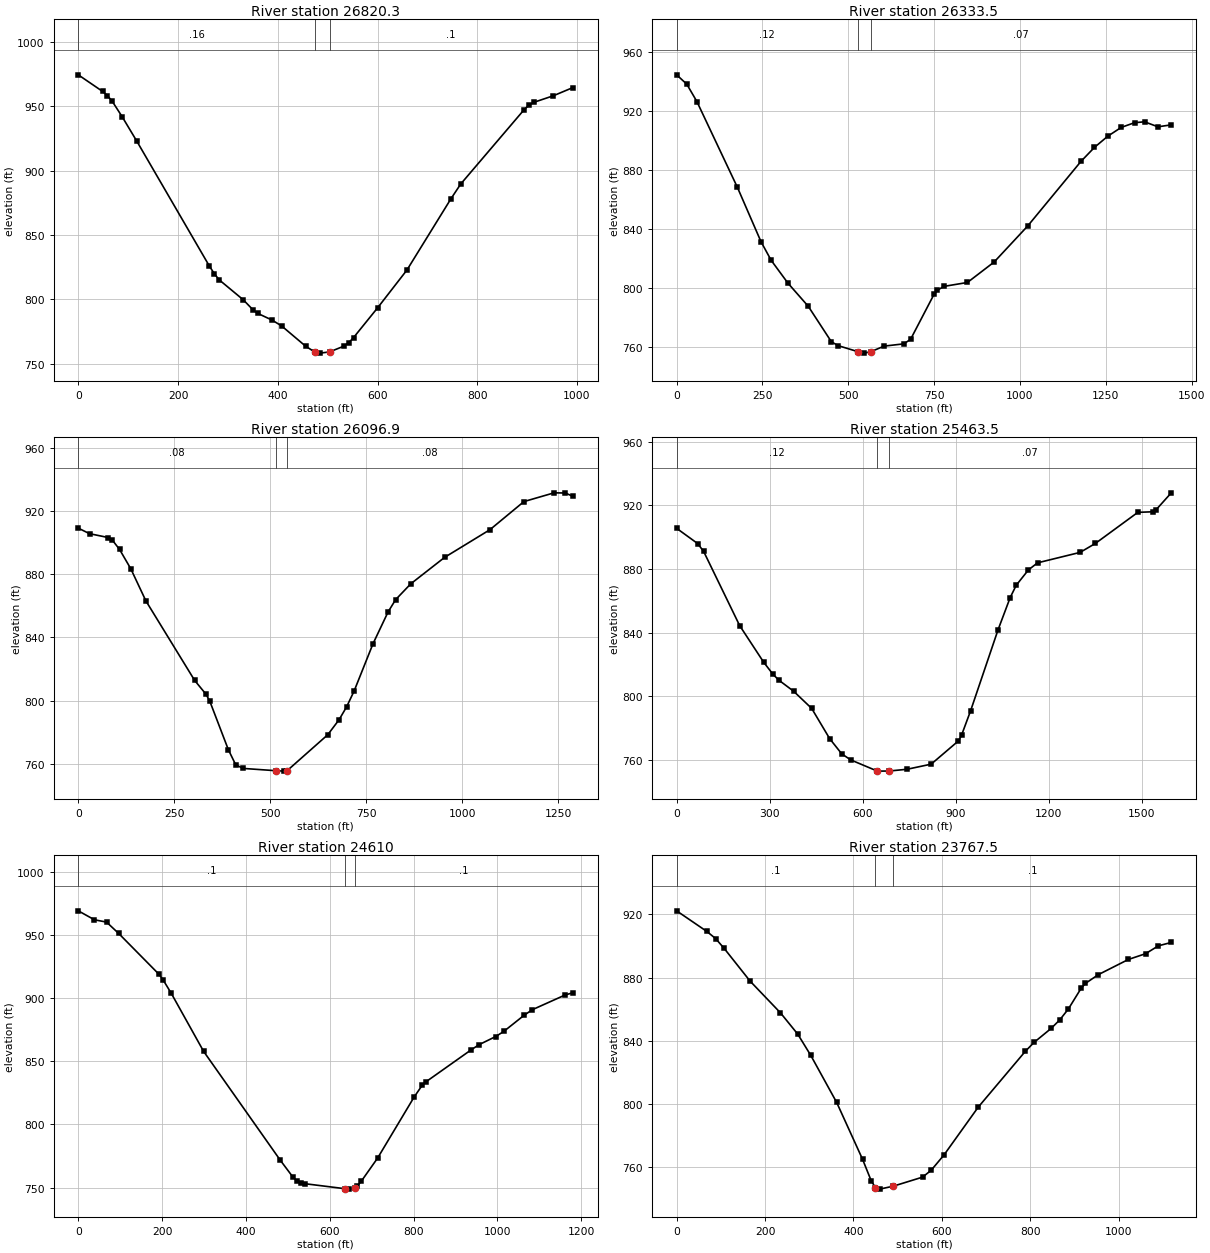
Type RM Length L Ch R = 1 ,26820.3 ,477.5,486.8,494.8
XS GIS Cut Line= 4
     1871958.711      595472.936       1872160.1      595684.741
     1872344.127      595906.963     1872594.127      596233.352
#Sta/Elev= 30
       0  974.25    48.7  961.39    58.4  958.16    68.2  953.65    87.7  941.92
   116.9  923.08     263   825.8   272.8  819.96   282.5  815.22   330.7  799.76
     350  792.08   359.6  789.22   388.4  784.01   407.7  779.46   455.8  763.74
     475  759.01   484.6  758.35   503.8  759.28   532.7  763.79   542.3  766.46
   551.9  770.38   600.4   793.6   659.1  822.87   747.2  878.08   766.8  889.52
     894  947.23   903.8   950.8   913.6  952.94   952.8  958.04   991.9  964.39
#Mann= 3 , 0 , 0
       0     .16       0     475    .045       0   503.8      .1       0
Bank Sta=475,503.8
XS Rating Curve= 0 ,0
Exp/Cntr=0.3,0.1

Type RM Length L Ch R = 1 ,26333.5 ,235.3,236.5,241.7
XS GIS Cut Line= 4
     1871844.127      595650.019     1871923.989      596025.019
      1872003.85      596271.547     1872580.239       596823.63
#Sta/Elev= 30
       0  944.38    29.5   938.1      59  926.31     177  868.22   245.8  831.38
   275.3  818.82   324.4  803.28   383.4  787.66   450.6   763.7   469.8  761.07
   527.4  756.98   546.6  755.95   565.8  756.94   604.2  760.69     662  762.24
   681.5  765.34   749.6  795.71   759.4  798.55   778.8  801.15     847  803.79
   924.8  817.65  1022.2  841.96  1177.9  885.84  1216.8  895.23  1255.8  902.84
  1294.7  908.76  1333.6  911.97  1362.8  912.57  1401.8  909.19  1440.7  910.51
#Mann= 3 , 0 , 0
       0     .12       0   527.4    .045       0   565.8     .07       0
Bank Sta=527.4,565.8
XS Rating Curve= 0 ,0
Exp/Cntr=0.3,0.1

Type RM Length L Ch R = 1 ,26096.9 ,634.8,633.4,627.2
XS GIS Cut Line= 4
     1871729.544      595684.741     1871746.905      596056.269
     1871760.794      596334.047     1871746.905      596972.936
#Sta/Elev= 30
       0  909.18    29.4  905.68    78.3  903.22    88.1  901.83   107.7  895.66
     137  883.38   176.2  863.11   303.4   812.7   332.8     804   342.6  799.67
   391.1  768.86   410.3  759.29   429.5  757.02   515.8  755.55     535   755.3
   544.6  755.65   650.1  778.34   679.6  787.85   699.2  795.98   718.9  806.09
     768  835.95   807.4  856.16     827   863.9   866.4  873.91   954.8   890.7
  1072.8  908.21  1161.3     926  1239.9  931.55  1269.4  931.44  1289.1   929.3
#Mann= 3 , 0 , 0
       0     .08       0   515.8    .045       0   544.6     .08       0
Bank Sta=515.8,544.6
XS Rating Curve= 0 ,0
Exp/Cntr=0.3,0.1

Type RM Length L Ch R = 1 ,25463.5 ,859.1,853.5,846.1
XS GIS Cut Line= 4
     1870927.461      595459.047     1871173.989      595931.269
      1871253.85      596177.797       1871535.1      596931.269
#Sta/Elev= 30
       0  905.56    67.8  895.99    87.2  891.04   203.4  844.44   280.9  821.42
   309.9  814.09   329.3  810.23   377.7  803.17   435.8   792.4     494  773.36
   532.7  763.87   561.5  760.08   647.9     753   686.3  753.07   743.8  754.18
   821.3  757.38   909.5  772.02   919.3  775.55   948.8  791.05    1037  841.73
  1076.3  862.07  1095.9  869.82  1135.1  879.42  1164.5  883.86  1301.8  890.43
  1350.9  896.02  1488.2  915.59  1537.2  915.95    1547  917.21  1596.1  927.85
#Mann= 3 , 0 , 0
       0     .12       0   647.9    .045       0   686.3     .07       0
Bank Sta=647.9,686.3
XS Rating Curve= 0 ,0
Exp/Cntr=0.3,0.1

Type RM Length L Ch R = 1 ,24610   ,832.5,842.5,852.3
XS GIS Cut Line= 4
     1870385.794       596229.88     1870646.211      596552.797
     1870833.711      596834.047     1871073.294      597188.213
#Sta/Elev= 30
       0   969.2    38.6   962.1    67.5  960.27    96.5  951.24     193  918.78
   202.6  914.39   221.9  903.84   299.1  857.85   482.4  771.44   511.4  758.62
   521.1  755.21   530.7  753.61   540.4  753.04     637  749.03   646.6  748.72
  660.62  749.94   665.9  751.23   675.6  755.11   714.2  773.29   801.4  821.69
   820.9  831.11   830.6  833.97   937.5  859.08   956.9  863.26   995.8  869.56
  1015.2  873.62  1063.8  886.44  1083.3  890.84    1161  902.42  1180.4  904.36
#Mann= 3 , 0 , 0
       0      .1       0     637    .045       0  660.62      .1       0
Bank Sta=637,660.62
XS Rating Curve= 0 ,0
Exp/Cntr=0.3,0.1

Type RM Length L Ch R = 1 ,23767.5 ,434.3,445.2,455.6
XS GIS Cut Line= 4
     1869889.266      596393.074     1869951.766      596799.324
     1869986.489      597038.908     1870114.961      597486.824
#Sta/Elev= 30
       0  922.26    68.5   909.2    88.1  904.75   107.6   898.5   166.4  877.77
   234.9  857.77     274  844.31   303.4  830.91   362.1  801.11   420.7  765.15
   440.1  751.65   449.8  747.25   459.4   746.3   490.5  748.19   556.3  753.88
   575.6  758.14   604.7  767.83   682.2  798.09     789  833.47   808.4  839.02
   847.3  847.92   866.7  853.28   886.1  860.14   915.2  873.31   924.9  876.38
   954.1  881.92    1022  891.51  1060.8  895.14    1090  900.15  1119.1  902.27
#Mann= 3 , 0 , 0
       0      .1       0   449.8    .045       0   490.5      .1       0
Bank Sta=449.8,490.5
XS Rating Curve= 0 ,0
Exp/Cntr=0.3,0.1