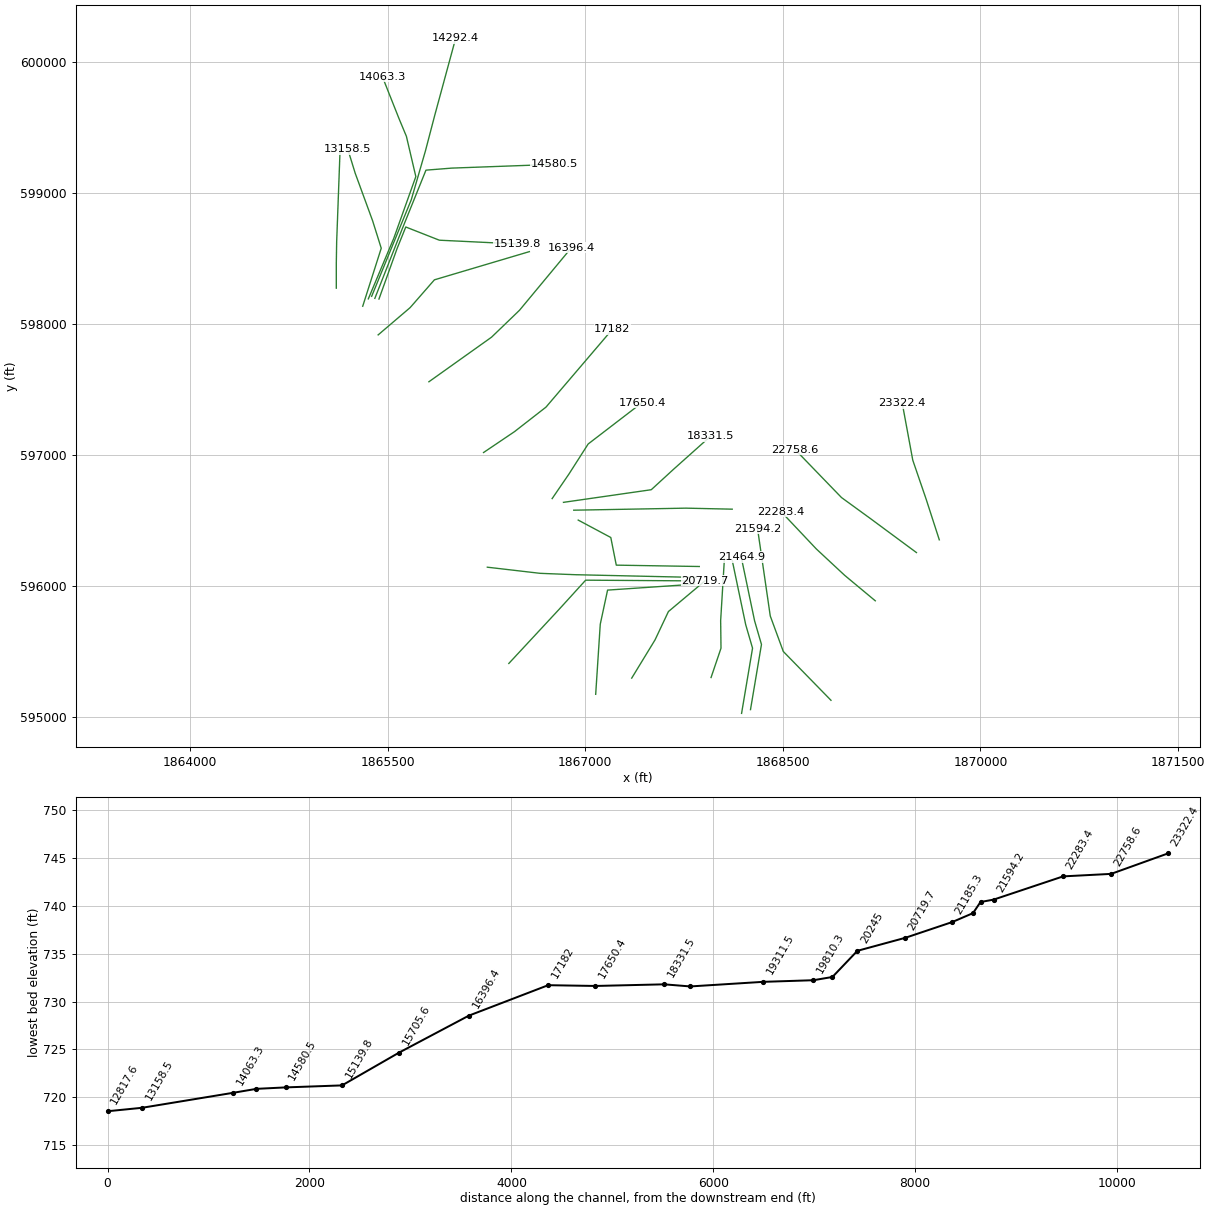
HEC-RAS study JohnsonCrk.prj: JohnsonCrk

--- JohnsonCrk.g01 (geometry) --- (continued)

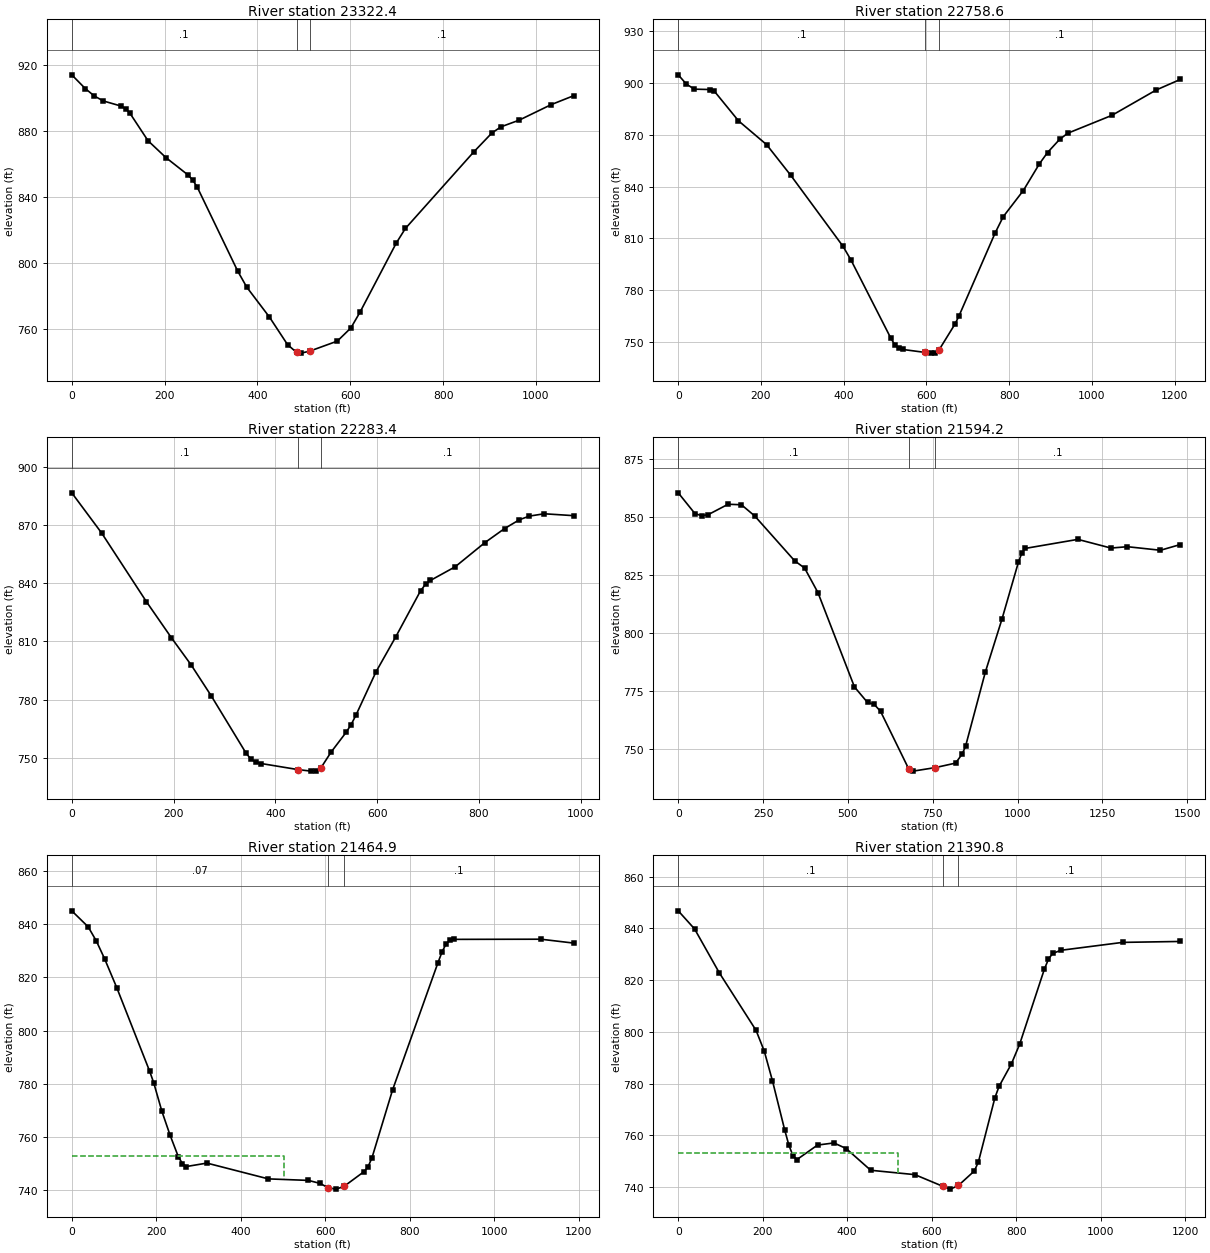
Type RM Length L Ch R = 1 ,23322.4 ,549.9,563.7,577.5
XS GIS Cut Line= 4
     1869687.877       596354.88     1869587.183       596667.38
     1869486.489      596962.519     1869406.627      597396.547
#Sta/Elev= 30
       0     914      29  905.71    48.3  901.25    67.6  898.21   106.2  895.08
   115.9  893.42   125.5  890.65   164.2  874.12   202.8  863.88   251.1  853.21
   260.7  850.21   270.4  845.92   357.6  795.05     377   785.4   425.8  767.31
   464.8  750.63   484.2  745.93     494  745.48   512.6  746.69     572  752.76
   601.2  760.72   620.7  770.18     699  812.14   718.6  820.95   865.7  867.25
     905  878.79   924.6  882.52   963.8  886.56  1032.4  895.92  1081.5   901.4
#Mann= 3 , 0 , 0
       0      .1       0   484.2    .045       0   512.6      .1       0
Bank Sta=484.2,512.6
XS Rating Curve= 0 ,0
Exp/Cntr=0.3,0.1

Type RM Length L Ch R = 1 ,22758.6 ,478.3,475.3,472.1
XS GIS Cut Line= 4
     1869514.266      596257.658     1869163.572      596518.074
     1868944.822      596677.797     1868594.127       597042.38
#Sta/Elev= 30
       0  904.82    19.4  899.51    38.8  896.51    77.7  896.28    87.4  895.28
   145.6  878.14   213.6   864.3   271.8  846.56     398   805.4   417.4  797.42
   514.2  751.84   523.9  748.06   533.5  746.06   543.2  745.45   596.4  743.76
   610.9  743.34   620.6  743.56   630.3  745.18     669  760.24   678.6  764.94
     766   813.1   785.5  822.51   834.1   837.7     873   853.2   892.5  859.72
   921.7  867.34   941.2  870.91  1048.2  881.31  1155.2  896.02  1213.5  902.15
#Mann= 3 , 0 , 0
       0      .1       0   596.4    .045       0   630.3      .1       0
Bank Sta=596.4,630.3
XS Rating Curve= 0 ,0
Exp/Cntr=0.3,0.1

Type RM Length L Ch R = 1 ,22283.4 ,699.2,689.2,678.9
XS GIS Cut Line= 4
     1869201.766      595889.602     1868969.127      596084.047
      1868753.85      596285.436     1868487.718      596568.711
#Sta/Elev= 30
       0   886.6    58.7  865.87   146.7  830.46   195.6  811.94   234.7  797.81
   273.9  781.98   342.5  752.35   352.3   749.2   362.2  747.68     372  747.01
   445.3  743.84   470.2  743.08   480.1  743.27   489.9  744.87   509.6  752.88
     539  763.03   548.9  767.02   558.7  772.06     598  794.34   636.9  812.43
   685.4  836.06   695.2  839.44   704.9  841.42   753.5  848.46   811.8  860.91
   850.6  868.18   879.8  872.73   899.2  874.59   928.4   875.8   986.7  874.82
#Mann= 3 , 0 , 0
       0      .1       0   445.3    .045       0   489.9      .1       0
Bank Sta=445.3,489.9
XS Rating Curve= 0 ,0
Exp/Cntr=0.3,0.1

Type RM Length L Ch R = 1 ,21594.2 ,130.8,129.3,127.7
XS GIS Cut Line= 4
     1868865.308      595130.444     1868503.329       595502.84
      1868404.37      595773.673     1868308.016      596438.604
#Sta/Elev= 30
       0  860.58      49  851.67    68.6  850.72    88.2  851.17     147  855.66
   186.2  855.44   225.4  850.61     343  831.29   372.4  828.16   411.6  817.62
   519.3  776.93   557.8  770.24     577   769.5   596.2  766.42  678.96  741.68
   692.3  740.65   757.9  742.18   817.4  744.11   836.9  748.04   846.6   751.3
     905  783.33   953.7     806  1002.4  830.64  1012.2  834.51  1021.9  836.61
  1177.7  840.52  1275.1  836.78  1323.8  837.36  1421.1  835.83  1479.6  838.29
#Mann= 3 , 0 , 0
       0      .1       0  678.96    .045       0   757.9      .1       0
Bank Sta=678.96,757.9
XS Rating Curve= 0 ,0
Exp/Cntr=0.3,0.1

Type RM Length L Ch R = 1 ,21464.9 ,74.1,74.1,74.1
XS GIS Cut Line= 4
     1868254.197      595059.264      1868337.53       595556.66
     1868285.447      595736.347     1868183.884      596223.326
#Sta/Elev= 30
       0  845.04    38.8  839.03    58.2  833.69    77.6  827.07   106.7  816.09
   184.3  784.78     194  780.41   213.4  769.66   232.8  760.68   252.2  752.64
   261.9  750.02   271.6   748.9     320  750.19   465.5  744.25   560.4  743.68
   588.5  742.53   607.2  740.89   625.9   740.4   644.6  741.42   691.4   746.9
   701.2  748.64   710.9   752.2   759.7  777.73     867  825.48   876.7  829.56
   886.5  832.64   896.2  834.06     906  834.31  1110.8  834.37  1188.9   832.9
#Mann= 3 , 0 , 0
       0     .07       0   607.2    .045       0   644.6      .1       0
#XS Ineff= 2 , 0
          501.67  752.94
Permanent Ineff=
       F       F
Bank Sta=607.2,644.6
XS Rating Curve= 0 ,0
Exp/Cntr=0.3,0.1

Type RM Length L Ch R = 1 ,21390.8 ,211.6,205.4,199.4
XS GIS Cut Line= 4
     1868186.489      595030.618     1868269.822      595528.014
     1868217.739      595707.701     1868116.176       596194.68
#Sta/Elev= 30
       0  846.83    38.8   839.8      97  822.93   184.3  800.61   203.7  792.59
   223.1  781.13   252.2  762.05   261.9  756.28   271.6  752.17   281.3  750.69
   329.8  756.27   368.6   757.1   397.6  754.94   455.8  746.53   560.4  744.84
   625.9  740.37   644.6  739.24   663.4  740.65   701.2  746.26   710.9  749.81
   749.9  774.59   759.7  778.96     789  787.69   808.5  795.28     867  824.28
   876.7  828.14   886.5  830.34     906  831.57  1052.3  834.63  1188.9  834.99
#Mann= 3 , 0 , 0
       0      .1       0   625.9    .045       0   663.4      .1       0
#XS Ineff= 2 , 0
          519.73  753.28
Permanent Ineff=
       F       F
Bank Sta=625.9,663.4
XS Rating Curve= 0 ,0
Exp/Cntr=0.3,0.1

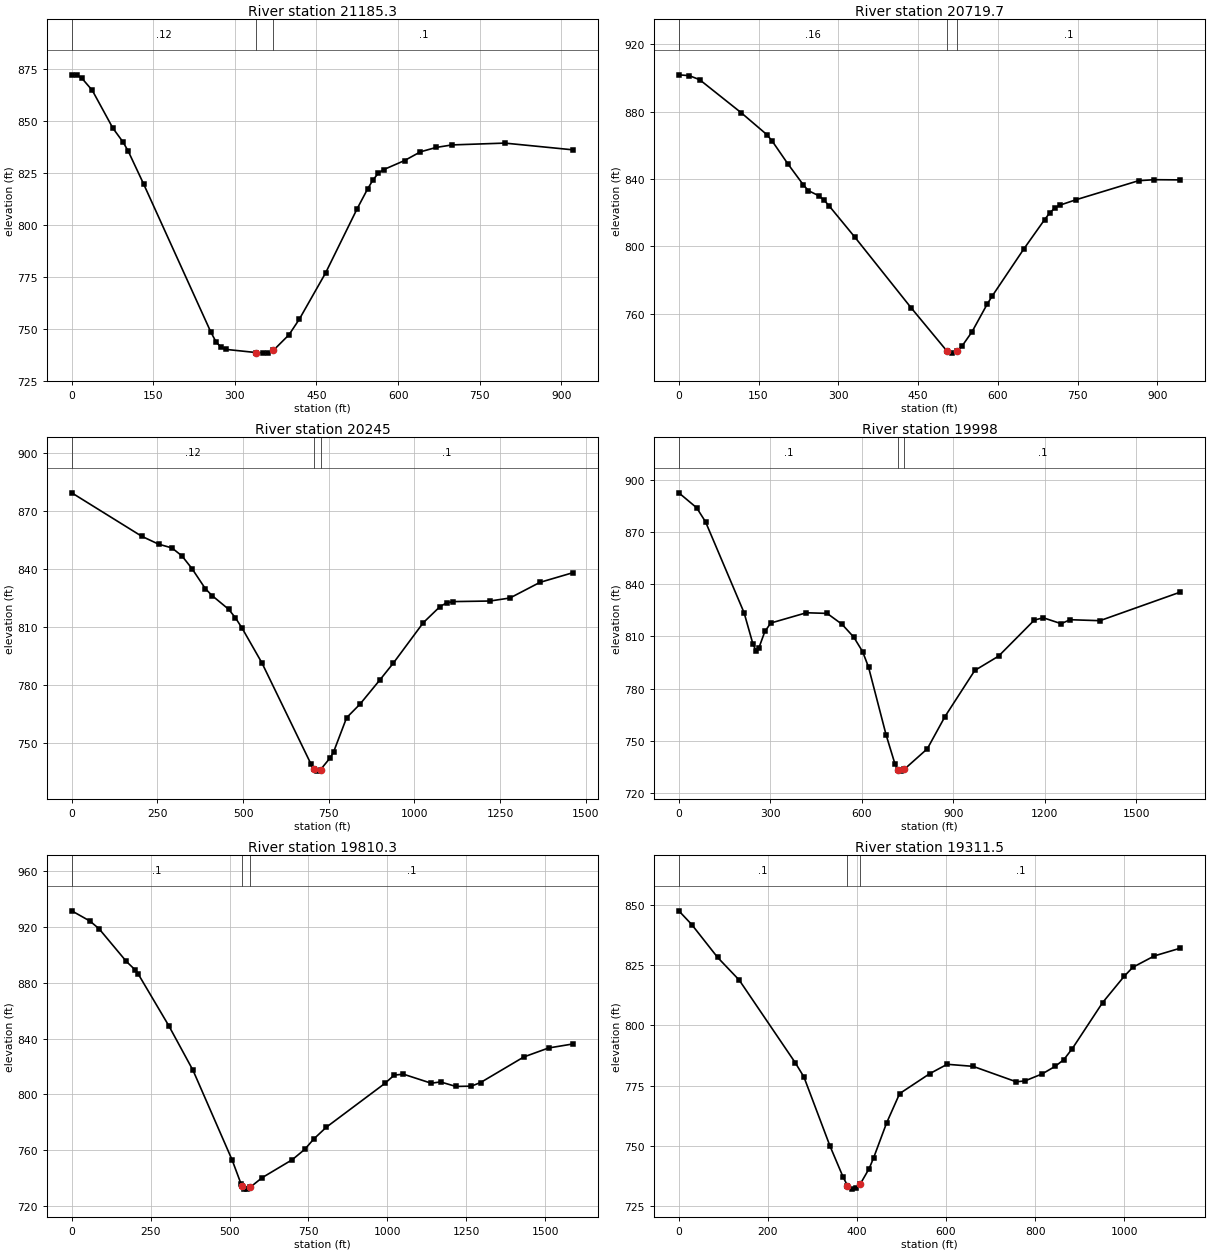
Type RM Length L Ch R = 1 ,21185.3 ,475.6,465.6,455.3
XS GIS Cut Line= 4
     1867954.718      595304.055     1868030.239      595528.014
     1868027.634      595738.951      1868056.28       596212.91
#Sta/Elev= 30
       0  872.24     9.4  872.26    18.9  870.54    37.8  864.77    75.6  846.61
    94.5  839.84     104  835.44   132.4  819.58   255.5  748.59   265.1  743.82
   274.7  741.04   284.3  740.09   339.6  738.57   351.4  738.31     361  738.48
   370.6  739.61   399.4  747.13   418.5  754.66   466.7  776.88   524.8  807.84
   544.2  817.43   553.9  821.66   563.6  824.88   573.3  826.61     612  831.01
   641.1  835.19   670.2  837.32   699.2  838.52   796.2   839.4   922.1  836.14
#Mann= 3 , 0 , 0
       0     .12       0   339.6    .045       0   370.6      .1       0
Bank Sta=339.6,370.6
XS Rating Curve= 0 ,0
Exp/Cntr=0.3,0.1

Type RM Length L Ch R = 1 ,20719.7 ,469.5,474.7,479.9
XS GIS Cut Line= 4
     1867352.287      595299.715      1867529.37      595591.382
     1867630.933      595807.528     1867908.725      596041.801
#Sta/Elev= 30
       0  901.94    19.5  901.46      39  899.08     117  879.51   165.7  866.39
   175.5  862.65   204.7  849.24     234  836.69   243.7  833.16   263.2  830.13
     273   827.6   282.7  824.12   331.5  805.38   436.7  763.68   503.6  738.16
   513.2  736.66   523.8  737.98   532.3  740.64   551.4  749.27     580  765.73
   589.8   770.7   648.8  798.45   688.1  815.95   697.9  820.02   707.7  822.96
   717.5  824.61     747  827.74   864.8  839.06   894.3  839.66   943.4  839.54
#Mann= 3 , 0 , 0
       0     .16       0   503.6    .045       0   523.8      .1       0
Bank Sta=503.6,523.8
XS Rating Curve= 0 ,0
Exp/Cntr=0.3,0.1

Type RM Length L Ch R = 1 ,20245   ,259.4,247,234.6
XS GIS Cut Line= 4
     1867078.682      595176.102     1867113.404      595710.824
      1867168.96       595971.24     1867828.682      596016.379
#Sta/Elev= 30
       0   879.5   204.6  856.95   253.3  852.91   292.3  850.95   321.5  846.83
   350.7  840.28   389.7  829.87   409.2   826.3   457.9  819.15   477.4   814.8
   496.9  809.43   554.9  791.39   697.5  739.19   707.4  736.25   716.5   735.3
     726  736.08   754.6  742.29   764.1  745.25   802.1  762.99     841  769.98
   899.4  782.61   938.3  791.24  1025.8  812.21  1074.4  820.52  1093.9  822.49
  1113.3  823.14  1220.3  823.44  1278.6     825  1366.1   833.1  1463.4  838.17
#Mann= 3 , 0 , 0
       0     .12       0   707.4    .045       0     726      .1       0
Bank Sta=707.4,726
XS Rating Curve= 0 ,0
Exp/Cntr=0.3,0.1

Type RM Length L Ch R = 1 ,19998   ,207.2,187.7,167.7
XS GIS Cut Line= 4
     1866419.142      595411.593     1866801.954      595825.655
     1867002.475       596047.01     1867783.725      596041.801
#Sta/Elev= 30
       0  892.57    58.3     884    87.5  875.92   213.9  823.62   243.1  805.52
   252.8   801.9   262.5  803.46     282  812.87   301.4  817.71   418.1  823.62
   486.1  823.25   534.7  817.03   573.5  809.58   602.4  801.26   621.7  792.41
   679.5  753.32   708.4   736.7   718.1  733.32   727.7  732.57   739.2  733.66
   814.4  745.41   872.4  763.95     970  790.45  1048.1  798.69  1165.3  819.42
  1194.6  820.73  1253.2  817.34  1282.5  819.62  1380.2  819.06  1643.8   835.5
#Mann= 3 , 0 , 0
       0      .1       0   718.1    .045       0   739.2      .1       0
Bank Sta=718.1,739.2
XS Rating Curve= 0 ,0
Exp/Cntr=0.3,0.1

Type RM Length L Ch R = 1 ,19810.3 ,528.8,498.8,468.7
XS GIS Cut Line= 4
     1866255.933      596146.069     1866656.975      596099.194
       1866922.6      596088.778      1867841.87      596067.944
#Sta/Elev= 30
       0  931.49    57.7  924.15    86.5  918.66     173  895.26   201.9  889.01
   211.5  885.91   307.6  849.18   384.5  817.18   508.2  753.09   536.7  735.81
     541  734.43   546.2  732.49   555.7  732.23   565.2  733.52   603.1   740.4
     699  753.34   738.1  760.67   767.4  768.23   806.6  776.55   992.4  807.95
  1021.8  813.87  1051.1  814.52  1139.1  808.06  1168.5  808.99  1217.4  805.74
  1266.3  805.97  1295.6  808.56  1432.6  826.88  1510.8  833.28  1589.1  836.21
#Mann= 3 , 0 , 0
       0      .1       0     541    .045       0   565.2      .1       0
Bank Sta=541,565.2
XS Rating Curve= 0 ,0
Exp/Cntr=0.3,0.1

Type RM Length L Ch R = 1 ,19311.5 ,690.2,722.2,754
XS GIS Cut Line= 4
     1866946.037      596505.444     1867193.433      596372.632
       1867235.1      596161.694     1867865.308      596151.278
#Sta/Elev= 30
       0  847.38      29  841.69    87.1  828.07   135.6  818.68   261.4  784.45
   280.8  778.57   339.4  749.92   368.8  737.09   378.5  733.56   388.3  732.06
   398.1  732.48   407.8  734.31   427.4   740.6   437.2  744.95   466.5  759.47
   495.8  771.65   563.7  779.94   602.5  783.79   660.6  782.94   757.6  776.54
     777  776.89   815.8   779.8   844.9  782.92   864.3  785.68   883.7  790.33
   951.6  809.37    1000  820.25  1019.4  823.99  1067.9  828.71  1126.1   831.9
#Mann= 3 , 0 , 0
       0      .1       0   378.5    .045       0   407.8      .1       0
Bank Sta=378.5,407.8
XS Rating Curve= 0 ,0
Exp/Cntr=0.3,0.1

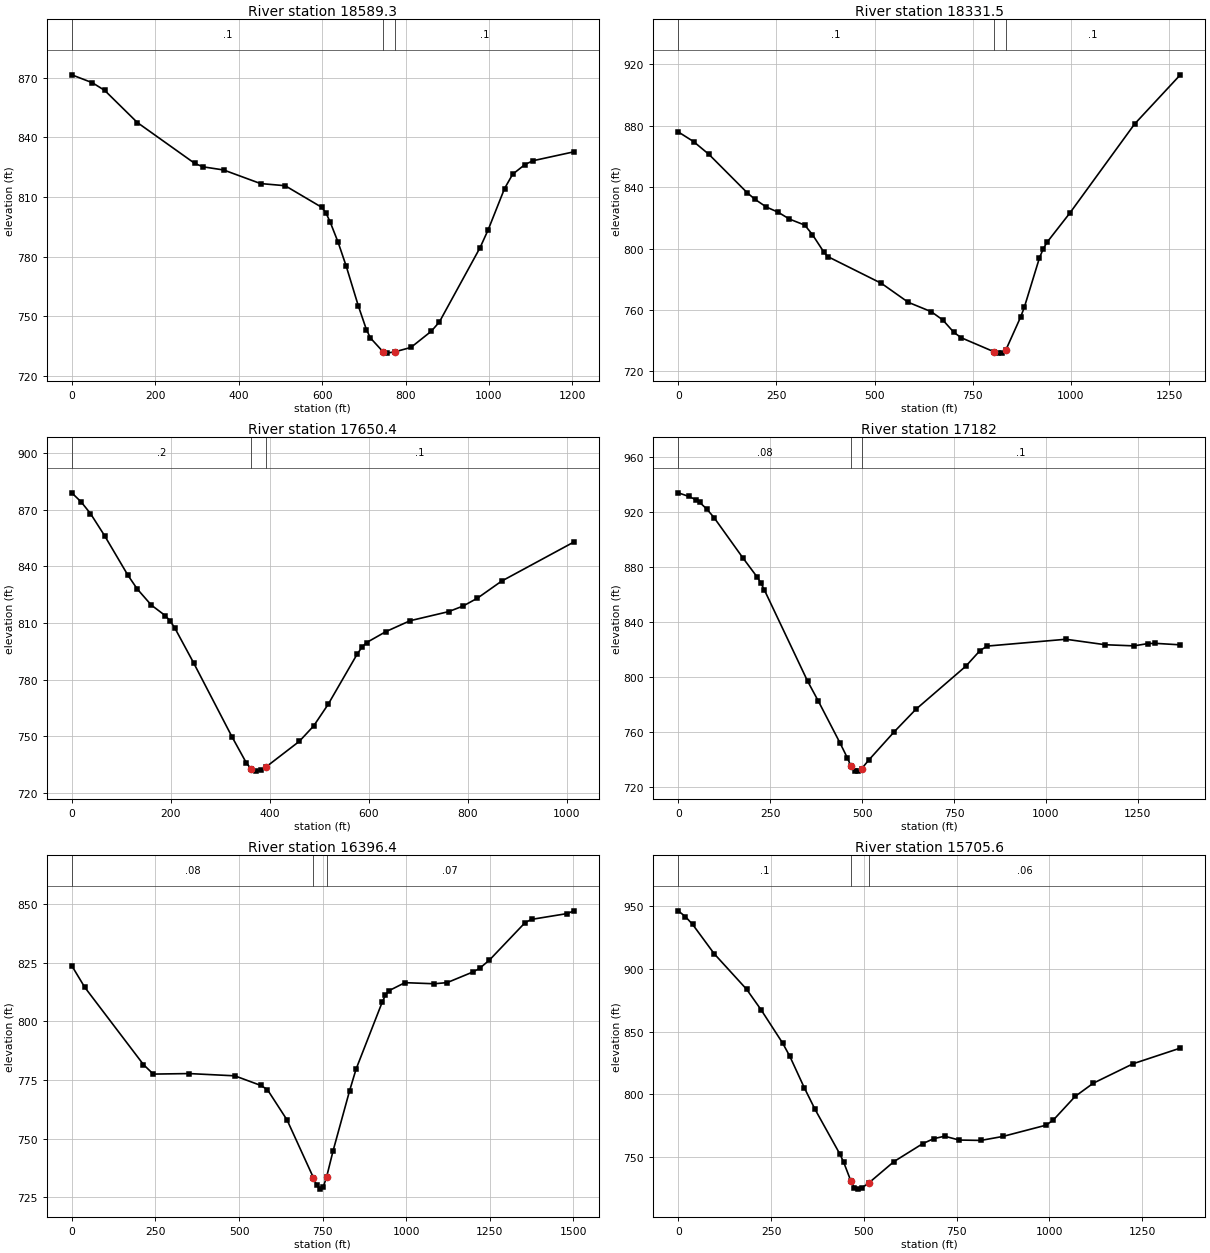
Type RM Length L Ch R = 1 ,18589.3 ,241.6,257.8,273.9
XS GIS Cut Line= 4
     1866912.183      596580.965     1867482.495      596591.382
     1867763.745       596596.59     1868115.308      596588.778
#Sta/Elev= 30
       0  871.41    49.2  867.45    78.7  863.62   157.4   847.4     295  826.87
   314.7  825.18   363.9  823.61   452.4  816.78   511.4   815.7   599.5   804.8
   609.2  802.02   618.9  797.68   638.3  787.32   657.7  775.34   686.8  755.34
   706.2   743.4   715.9  739.17     746  732.29   754.7  731.58   774.1  732.22
   812.9  734.44   861.5  742.54     881   747.2   978.7  784.61   998.2  793.62
  1037.3  814.28  1056.8  821.48  1086.1  826.32  1105.7  828.26  1203.4  832.72
#Mann= 3 , 0 , 0
       0      .1       0     746    .045       0   774.1      .1       0
Bank Sta=746,774.1
XS Rating Curve= 0 ,0
Exp/Cntr=0.3,0.1

Type RM Length L Ch R = 1 ,18331.5 ,674.4,681,687.1
XS GIS Cut Line= 4
     1866834.058      596640.861     1867500.725      596737.215
     1867667.391      596890.861     1867948.641      597143.465
#Sta/Elev= 30
       0  876.01      39   869.7    78.1  861.38   175.7  836.32   195.2  832.11
   224.5     827   253.8  823.74   283.1  819.18   322.2  815.25   341.7  809.05
     371  797.56   380.7  794.74   517.4  777.27   585.7  764.93   644.3   758.8
   673.6  753.41   701.9  745.29   720.8   741.8   804.1  732.67   815.3   731.8
   824.7  731.96   834.2   733.9   871.9  755.41   881.4   761.9   919.7  793.91
   929.4  799.82     939  804.07   997.2  823.16    1162  881.18  1278.3  913.21
#Mann= 3 , 0 , 0
       0      .1       0   804.1    .045       0   834.2      .1       0
Bank Sta=804.1,834.2
XS Rating Curve= 0 ,0
Exp/Cntr=0.3,0.1

Type RM Length L Ch R = 1 ,17650.4 ,476.1,468.4,460.7
XS GIS Cut Line= 4
      1866748.12      596669.507     1866875.725      596857.007
     1867021.558      597086.173     1867430.412      597401.278
#Sta/Elev= 30
       0  878.98    18.9  874.19    37.8     868    66.2  856.34   113.4  835.37
   132.3  828.07   160.6  819.58     189  813.95   198.4  811.26   207.9  807.58
   246.2  788.96   323.8   749.8   352.9  735.93   362.6  732.78   372.3  731.63
     382   732.1   391.7  733.68   459.6  747.35   488.7  755.51   517.9  766.91
   576.4  793.43   586.1  797.15   595.8   799.7   634.8   805.5   683.5  811.25
   761.4  816.07   790.6  819.01   819.8  823.21   868.5  832.21  1014.6  852.92
#Mann= 3 , 0 , 0
       0      .2       0   362.6    .045       0   391.7      .1       0
Bank Sta=362.6,391.7
XS Rating Curve= 0 ,0
Exp/Cntr=0.3,0.1

Type RM Length L Ch R = 1 ,17182   ,783,785.6,787.8
XS GIS Cut Line= 4
     1866227.287      597021.069     1866461.662      597179.923
     1866701.245      597367.423     1867204.718      597960.305
#Sta/Elev= 30
       0  934.12    29.3  931.46    48.8     929    58.6  927.12    78.1  922.18
    97.6  916.02   175.7  886.84   214.8   872.8   224.6   868.6   234.3  863.43
   351.8  797.11   381.3  782.45   440.2  752.03   459.8  741.38   469.6  735.46
   479.4  731.98   489.2  731.71     499  733.58   518.7  739.95   587.4  760.35
   645.7  776.55   781.8  807.98   820.7  819.42   840.2  822.66  1054.1  827.62
    1161  823.64  1238.8  822.81  1277.7  824.49  1297.1  824.65  1365.2  823.56
#Mann= 3 , 0 , 0
       0     .08       0   469.6    .045       0     499      .1       0
Bank Sta=469.6,499
XS Rating Curve= 0 ,0
Exp/Cntr=0.3,0.1

Type RM Length L Ch R = 1 ,16396.4 ,688.6,690.9,691.8
XS GIS Cut Line= 4
     1865812.357         597561.     1866288.051      597901.278
     1866499.857      598106.139      1866895.69      598585.305
#Sta/Elev= 30
       0  823.74      39   814.5   214.4  781.59   243.7  777.55   350.9  777.77
   487.4  776.81   565.4   772.7   584.9  770.94   643.8  757.96   722.4  733.43
   732.2  730.25     742  728.53   751.8  729.44   761.7  733.59   781.3  744.87
   830.4  770.34   850.1  779.71   928.1  808.19   937.8   811.2   947.5  813.03
   996.1  816.51  1083.5  816.04  1122.3  816.53    1200   821.1  1219.4  822.61
  1248.6  826.12  1355.4   842.1  1374.8  843.48  1481.6  845.96  1501.1  847.12
#Mann= 3 , 0 , 0
       0     .08       0   722.4    .045       0   761.7     .07       0
Bank Sta=722.4,761.7
XS Rating Curve= 0 ,0
Exp/Cntr=0.3,0.1

Type RM Length L Ch R = 1 ,15705.6 ,592.9,565.7,538.2
XS GIS Cut Line= 4
      1865426.94      597918.639     1865669.995      598126.972
     1865854.023      598338.778     1866574.871      598553.838
#Sta/Elev= 30
       0  946.05    19.4   941.4    38.8  935.22      97  911.87   184.3  883.62
   223.1   867.4   281.3  840.86   300.7  830.33   339.5  805.45   368.5  788.21
   436.2  752.23   445.9  746.01   465.2  731.14   474.9  725.69   484.6  724.67
   494.3  725.54   513.6  729.61   581.4  746.59   659.3  760.93   688.6  764.81
   717.9  766.77     757  763.72   815.6  763.42   874.2  766.54   991.5  775.57
    1011   779.7  1069.6  798.43  1118.5  808.94    1226  824.44    1353  836.85
#Mann= 3 , 0 , 0
       0      .1       0   465.2    .045       0   513.6     .06       0
Bank Sta=465.2,513.6
XS Rating Curve= 0 ,0
Exp/Cntr=0.3,0.1

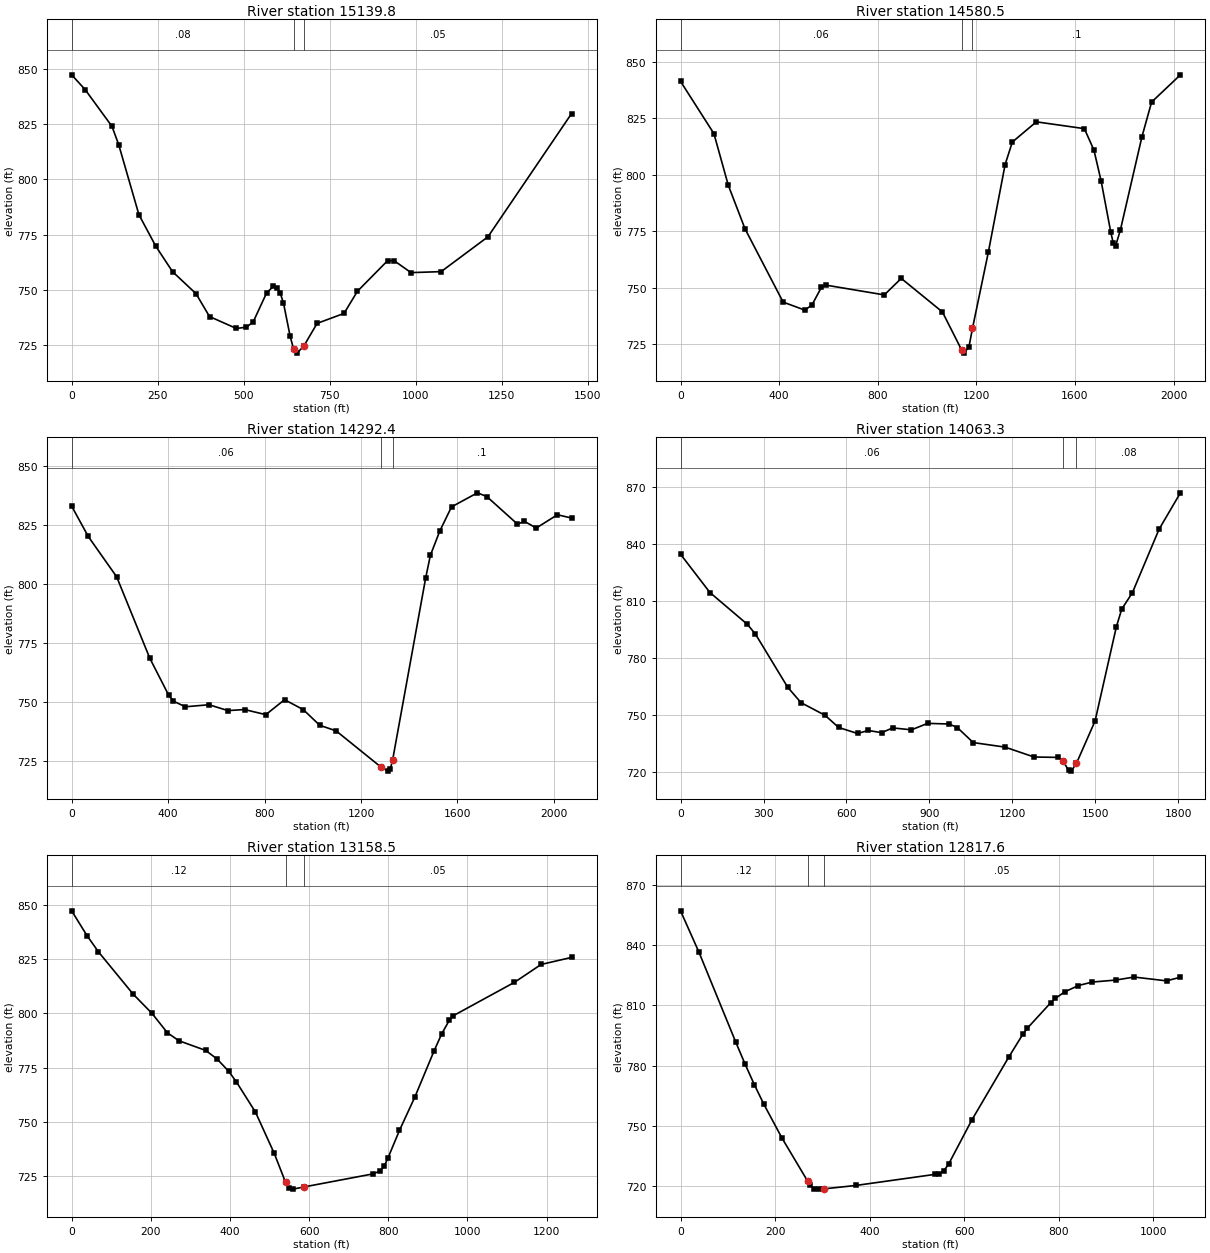
Type RM Length L Ch R = 1 ,15139.8 ,549.3,559.3,569.4
XS GIS Cut Line= 5
     1865433.016      598192.076     1865571.052      598578.694
      1865636.59      598741.888     1865891.364      598641.194
     1866483.725      598612.432
#Sta/Elev= 30
       0  847.38    39.1   840.7   117.3  823.99   136.8  815.72   195.5     784
   244.4  769.75   293.2  758.18   361.6  748.17   400.8  737.82   478.9  732.42
   508.2  733.01   527.8   735.4   566.8  748.53   586.4  751.51   596.2  750.83
     606  748.63   615.7  744.04   635.3  728.84   645.1  723.16   654.9  721.24
   674.4   724.3   713.6  734.72   791.8  739.24     831   749.3   918.7  763.17
   938.1  763.08   986.7  757.73  1074.2  758.18  1210.3  773.96  1453.4  829.81
#Mann= 3 , 0 , 0
       0     .08       0   645.1    .045       0   674.4     .05       0
Bank Sta=645.1,674.4
XS Rating Curve= 0 ,0
Exp/Cntr=0.3,0.1

Type RM Length L Ch R = 1 ,14580.5 ,259,288.1,316.7
XS GIS Cut Line= 5
     1865401.766      598197.285     1865606.627      598719.854
     1865789.787      599175.583       1865985.1      599191.208
     1866763.745      599219.854
#Sta/Elev= 30
       0  841.28   135.5  818.13   193.6  795.34   261.3  776.09   416.1  743.61
   503.2   740.1   532.3  742.18   571.1  750.08   590.8   751.1   826.5  746.79
   895.3  754.09  1062.2  739.25  1140.6  722.34  1150.4  721.03    1170  723.89
  1184.2  732.02  1248.4  765.62  1316.6  804.48  1345.8  814.42  1443.2  823.36
    1638  820.35  1676.9  810.82  1706.2  797.08  1745.1  774.54  1754.8   769.9
  1764.6  768.43  1784.1   775.5  1871.7  816.85  1910.7   832.1  2027.6  844.16
#Mann= 3 , 0 , 0
       0     .06       0  1140.6    .045       0  1184.2      .1       0
Bank Sta=1140.6,1184.2
XS Rating Curve= 0 ,0
Exp/Cntr=0.3,0.1

Type RM Length L Ch R = 1 ,14292.4 ,219,229.2,242.7
XS GIS Cut Line= 5
     1865377.461       598212.91     1865678.256      598949.353
     1865785.895      599322.617     1865857.495      599597.458
     1866015.409      600181.443
#Sta/Elev= 30
       0  833.14    68.8  820.28   186.6  803.19   324.1  768.69   402.7  752.98
   422.3  750.51   471.4  748.14   569.6     749   648.2  746.52   716.9  746.97
   805.2   744.8   882.9  751.14   960.6  746.93  1028.6   740.3  1096.6  737.94
  1281.9  722.66  1311.3  720.88  1321.1   721.7  1330.9  725.57    1468  802.69
  1487.5  812.27  1526.5  822.57  1575.3  832.82  1682.7  838.77  1721.7  837.18
  1848.5  825.53  1877.8  826.67  1926.6  823.86  2014.4  829.48    2073  828.09
#Mann= 3 , 0 , 0
       0     .06       0  1281.9    .045       0  1330.9      .1       0
Bank Sta=1281.9,1330.9
XS Rating Curve= 0 ,0
Exp/Cntr=0.3,0.1

Type RM Length L Ch R = 1 ,14063.3 ,903.2,904.7,903.2
XS GIS Cut Line= 6
     1865352.215      598193.451     1865546.312      598657.687
     1865712.979      599126.437     1865641.277      599433.902
     1865586.243      599566.541     1865458.638      599889.458
#Sta/Elev= 30
       0  834.57   106.4  814.41   241.9  797.65   270.9  792.55   387.1  764.67
   435.4  756.51   522.7  749.81   571.5  743.45   639.8  740.27   678.8  741.85
   727.5  740.69   766.6  743.21   834.8   742.2   893.4   745.6   971.4  745.25
  1000.7  743.39  1058.1  735.49  1172.9  733.11  1278.1   727.9  1364.3  727.69
  1382.5  725.96  1402.6  720.88  1412.1  720.47  1431.3  724.55  1498.6  746.84
  1575.7  796.44    1595  805.69  1633.6  814.35    1730  847.71  1807.2  866.87
#Mann= 3 , 0 , 0
       0     .06       0  1382.5    .045       0  1431.3     .08       0
Bank Sta=1382.5,1431.3
XS Rating Curve= 0 ,0
Exp/Cntr=0.3,0.1

Type RM Length L Ch R = 1 ,13158.5 ,348.2,341,333.6
XS GIS Cut Line= 5
      1865309.68      598137.172     1865450.305       598579.88
     1865385.201      598788.213     1865252.388      599152.797
     1865195.965       599336.68
#Sta/Elev= 30
       0  847.34    38.7  835.92    67.7  828.41   154.8  809.01   203.2  799.96
   241.9  791.06     271  787.38   338.7  782.91   367.7  778.91   396.8  773.29
   416.1  768.43   464.5  754.42     512  735.35   540.4  722.06   549.9  719.48
   559.4   718.9   587.9  719.94   760.4   725.9   779.8  727.26   789.5  729.42
   799.2  733.27   828.3  746.02   867.1  761.38   915.6  782.64     935  790.57
   954.4  796.88   964.1  798.91  1118.9  814.35  1186.2  822.59  1263.1  825.84
#Mann= 3 , 0 , 0
       0     .12       0   540.4    .045       0   587.9     .05       0
Bank Sta=540.4,587.9
XS Rating Curve= 0 ,0
Exp/Cntr=0.3,0.1

Type RM Length L Ch R = 1 ,12817.6 ,472.9,465.2,457.1
XS GIS Cut Line= 4
     1865109.159      598275.193     1865109.159      598470.505
     1865111.763      598626.755     1865137.805      599332.484
#Sta/Elev= 30
       0  856.92    39.1  836.29   117.2  791.46   136.7  780.65   156.2  770.49
   175.8  760.98   214.8  743.88   268.7  722.62   273.4  720.78   283.2  718.77
     293  718.54   302.8  718.65   371.2  720.37     538  725.86   547.8   726.3
   557.6  727.79   567.4  731.03   616.4  752.91   694.9  784.33   724.3  795.53
   734.1  798.61   783.2  811.18     793  813.34   812.6  816.58     842  819.78
   871.4  821.51   920.5  822.48   959.7  823.99  1028.4   822.1  1057.8  823.92
#Mann= 3 , 0 , 0
       0     .12       0   268.7    .045       0   302.8     .05       0
Bank Sta=268.7,302.8
XS Rating Curve= 0 ,0
Exp/Cntr=0.3,0.1