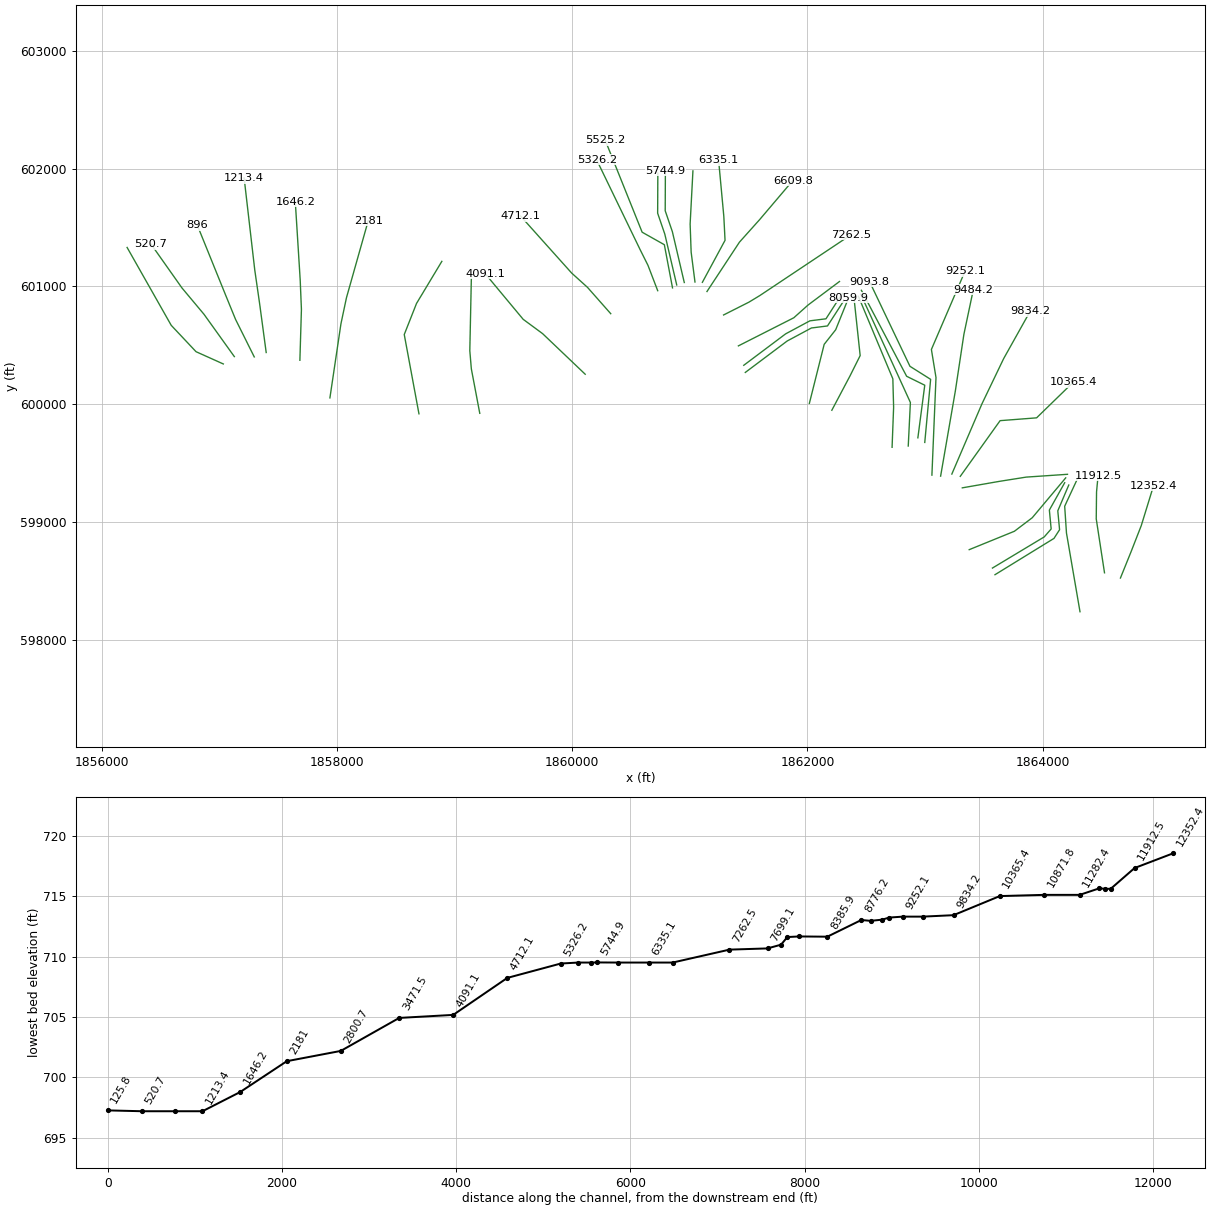
HEC-RAS study JohnsonCrk.prj: JohnsonCrk

--- JohnsonCrk.g01 (geometry) --- (continued)

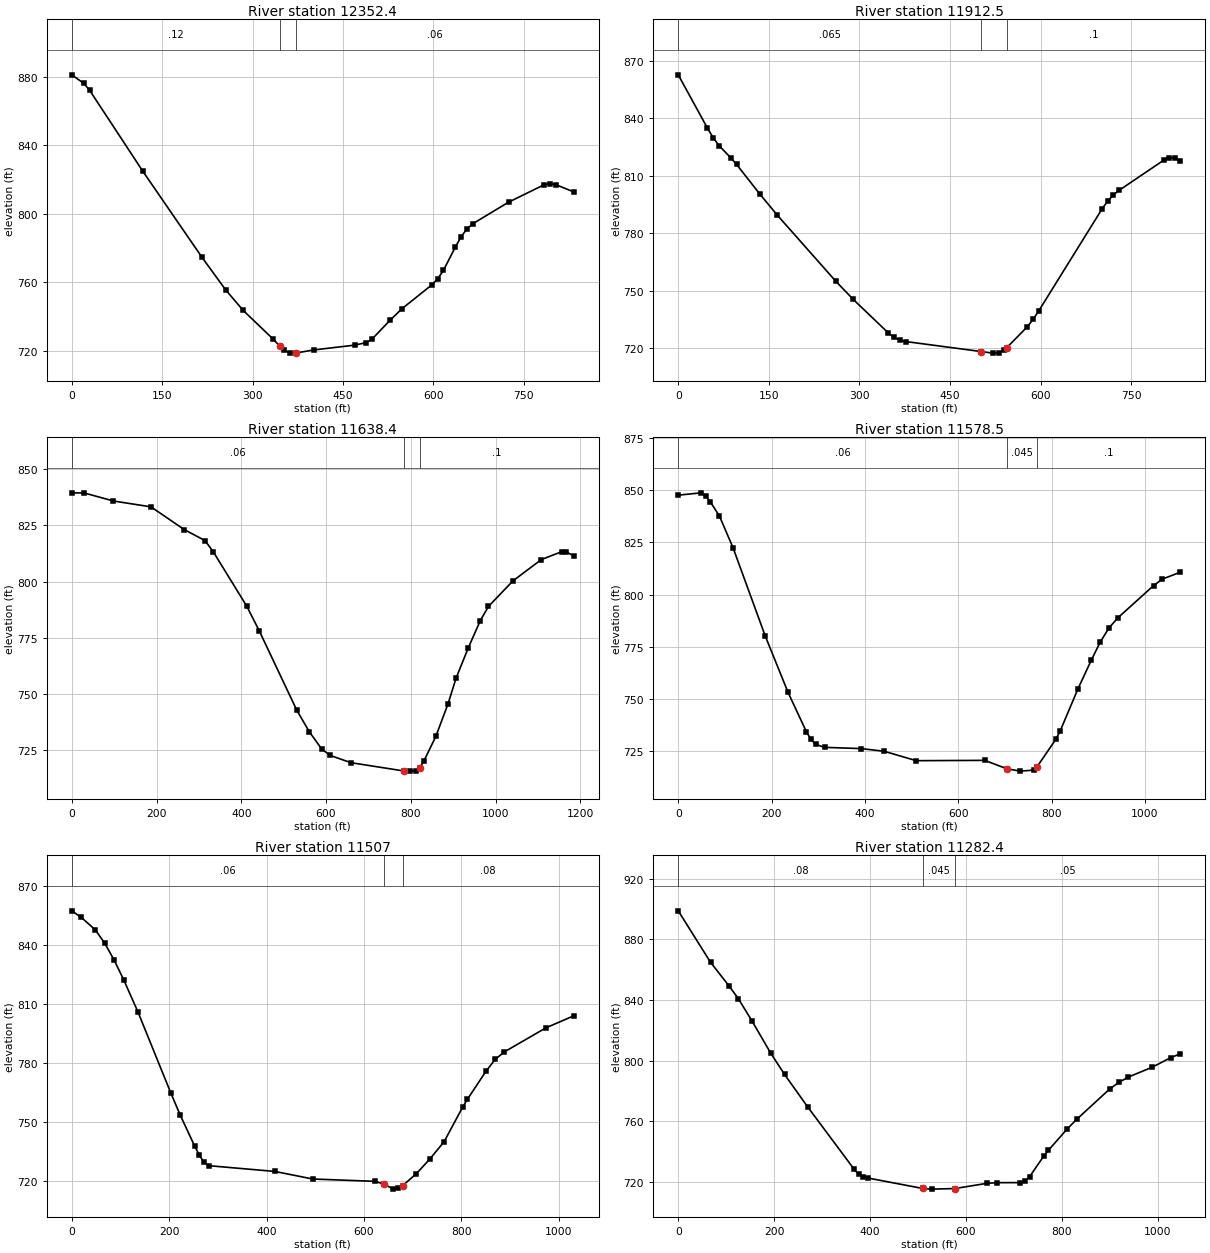
Type RM Length L Ch R = 1 ,12352.4 ,431.8,439.9,447.5
XS GIS Cut Line= 4
     1864661.243      598522.588     1864749.784      598741.338
     1864838.326      598967.901     1864942.493      599306.443
#Sta/Elev= 30
       0  881.05    19.7  876.14    29.5   872.1     118  824.71   216.3   774.4
   255.4   755.5   284.6  743.45   333.3  727.04   345.4  722.57   352.8  720.12
   362.5  718.53   372.2  718.61   401.4  720.38   469.5  723.19   489.1  724.69
   498.9  726.89   528.4  737.75   548.1  744.46   597.3  758.28   607.2   761.8
     617   766.9   636.7  780.47   646.5  786.62   656.3   791.2   666.2  794.21
   725.2  806.71   784.2  816.87   794.1  817.56   803.9  816.86   833.4  812.65
#Mann= 3 , 0 , 0
       0     .12       0   345.4    .045       0   372.2     .06       0
Bank Sta=345.4,372.2
XS Rating Curve= 0 ,0
Exp/Cntr=0.3,0.1

Type RM Length L Ch R = 1 ,11912.5 ,272.4,274.1,275.6
XS GIS Cut Line= 4
     1864525.826      598566.859     1864455.513      599025.193
     1864458.118      599254.359     1864471.138       599392.38
#Sta/Elev= 30
       0  862.65    48.3  834.87      58  829.75    67.6  825.68    86.9  819.37
    96.6  815.86   135.2  800.35   164.2  789.32   260.8   754.9   289.8  745.38
   347.8   727.9   357.4  725.51   367.1  724.05   376.8  723.37   501.9  718.14
     521  717.32   530.5   717.5   540.1  718.93   544.2  720.21   578.3  731.17
   587.8  734.96   597.4  739.56   702.1  792.72   711.4  796.74   720.6   799.9
   729.8  802.26   803.8  818.02     813  819.45   822.3  819.25   831.5   817.7
#Mann= 3 , 0 , 0
       0    .065       0   501.9    .045       0   544.2      .1       0
Bank Sta=501.9,544.2
XS Rating Curve= 0 ,0
Exp/Cntr=0.3,0.1

Type RM Length L Ch R = 1 ,11638.4 ,59.2,59.9,60.8
XS GIS Cut Line= 4
     1864317.493       598236.13     1864202.475      598904.533
     1864187.284      599132.397     1864304.472      599384.568
#Sta/Elev= 30
       0  839.53    29.5  839.46    98.3  835.89   186.8  833.29   265.4  823.16
   314.5  818.26   334.2  813.17   412.8  789.08   442.3  778.11   530.8  742.78
   560.3  733.18   589.8  725.44   609.4  722.62   658.6  719.36   782.9  715.69
   797.8   715.6   811.4  715.83     821  717.12   830.5  719.98     859  731.04
   887.6  745.44   906.6   756.9   935.4  770.41   964.1  782.67   983.3  788.95
  1040.8  800.28    1108  809.82  1155.9   813.3  1165.5  813.33  1184.7  811.43
#Mann= 3 , 0 , 0
       0     .06       0   782.9    .045       0     821      .1       0
Bank Sta=782.9,821
XS Rating Curve= 0 ,0
Exp/Cntr=0.3,0.1

Type RM Length L Ch R = 1 ,11578.5 ,71.4,71.5,71.4
XS GIS Cut Line= 5
     1863594.836        598550.8     1864096.138       598858.96
     1864143.881      598932.745      1864128.69      599093.335
     1864222.006      599312.519
#Sta/Elev= 30
       0  847.64      49  848.76    58.8  847.14    68.6  844.49    88.3  837.64
   117.7  822.32   186.3  780.34   235.4  753.24   274.6  734.45   284.4  730.83
   294.2   728.4   313.8  726.97   392.3  726.38   441.3   725.1     510   720.6
   656.8  720.75   704.8  716.68   733.3   715.6   761.7   716.1   768.3  717.49
   809.2  730.84   818.7  734.94   856.7  755.04   885.3  768.76   904.3  777.35
   923.4  784.23   942.4  789.02  1018.7  804.39  1037.7   807.5  1075.9  810.78
#Mann= 3 , 0 , 0
       0     .06       0   704.8    .045       0   768.3      .1       0
Bank Sta=704.8,768.3
XS Rating Curve= 0 ,0
Exp/Cntr=0.3,0.1

Type RM Length L Ch R = 1 ,11507   ,248,224.6,200.5
XS GIS Cut Line= 5
     1863573.135      598607.224     1864013.673      598871.981
     1864072.267      598939.255     1864057.076      599099.845
     1864187.284       599332.05
#Sta/Elev= 30
       0  857.46    19.4  854.14    48.5  847.72    67.9  840.86    87.3   832.2
   106.7  822.26   135.8  805.96   203.6  764.47     223  753.17   252.1  737.66
   261.8     733   271.5  729.26   281.2  727.59     417  724.65   494.6   720.8
   622.2  719.61   641.1  718.19   660.1  715.64   669.6  716.05   679.1  717.38
   707.6  723.55     736  731.24   764.5  739.86   802.5  757.47     812  761.33
   850.1  775.63   869.1  781.73   888.1  785.58   973.7  797.88  1030.7  803.96
#Mann= 3 , 0 , 0
       0     .06       0   641.1    .045       0   679.1     .08       0
Bank Sta=641.1,679.1
XS Rating Curve= 0 ,0
Exp/Cntr=0.3,0.1

Type RM Length L Ch R = 1 ,11282.4 ,421.1,410.6,399.5
XS GIS Cut Line= 4
     1863375.652      598763.474     1863759.767      598919.724
     1863911.677      599034.741     1864195.965      599373.283
#Sta/Elev= 30
       0  898.83    67.5   864.8   106.1  849.18   125.4  840.82   154.3  825.89
   192.9  804.87   221.8  790.78     270  769.39   366.5  728.38   376.1  724.86
   385.8  723.16   395.4  722.45     510  715.54     529   715.1   576.6  715.48
   644.5  718.94   664.2  719.37   713.3  719.39   723.1  720.49   732.9  723.32
   762.4  736.89   772.2  740.74   811.5   754.9   831.2  761.17   899.9  781.18
   919.6  785.64   939.2  789.13   988.4  795.55  1027.6  801.94  1047.3  804.45
#Mann= 3 , 0 , 0
       0     .08       0     510    .045       0   576.6     .05       0
Bank Sta=510,576.6
XS Rating Curve= 0 ,0
Exp/Cntr=0.3,0.1

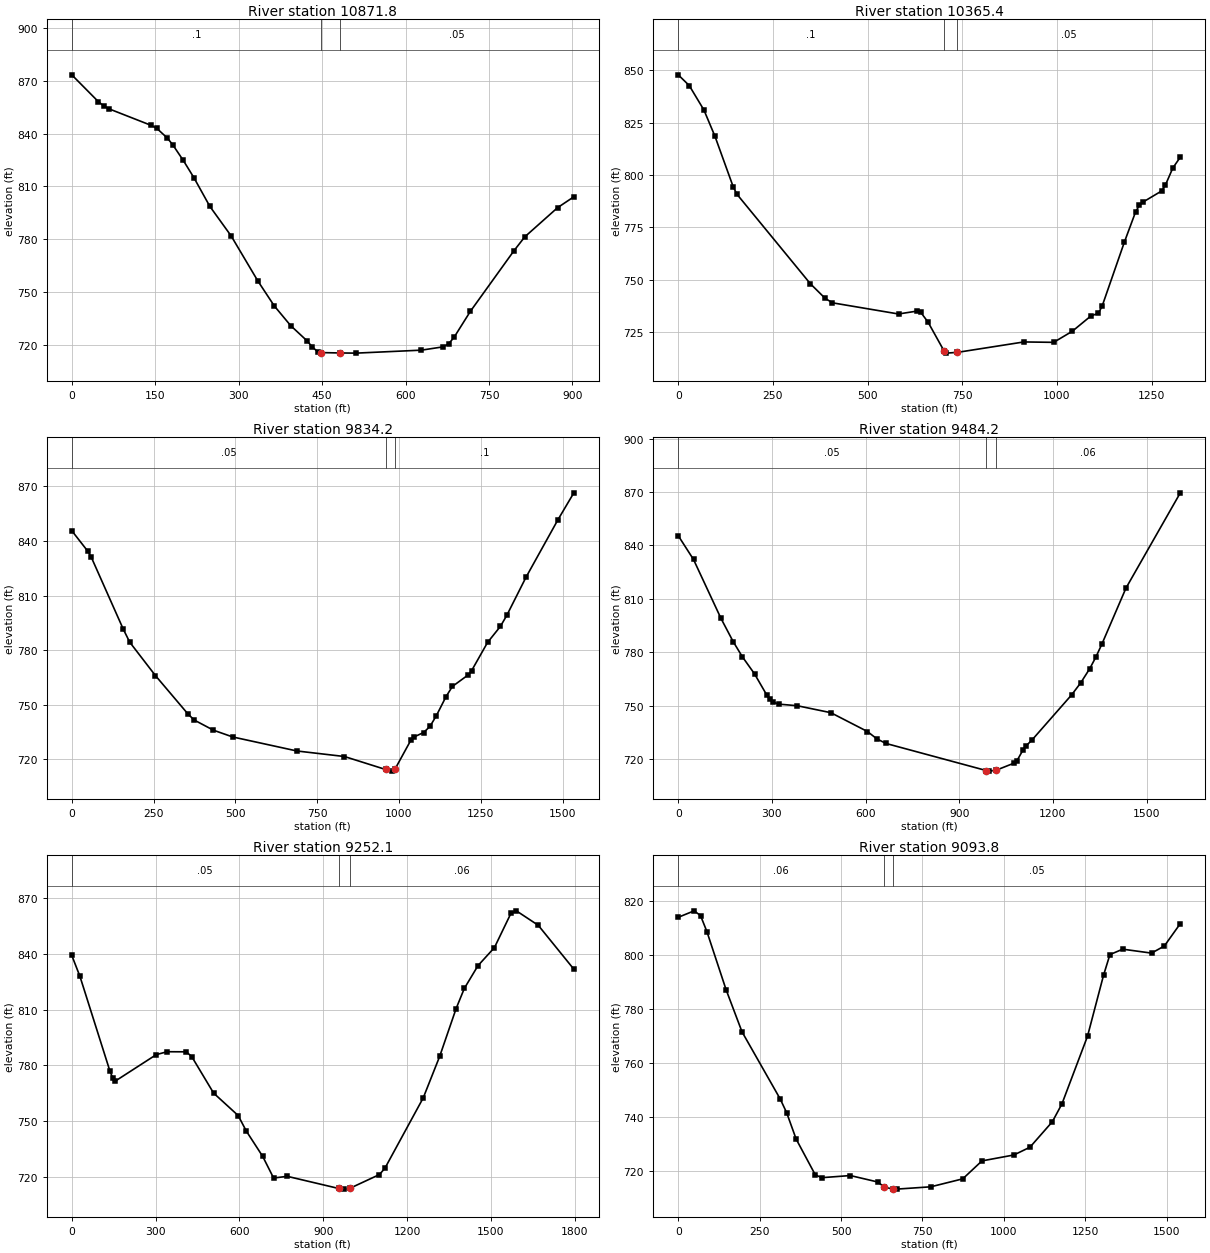
Type RM Length L Ch R = 1 ,10871.8 ,508.1,506.4,504.8
XS GIS Cut Line= 4
     1863317.059      599288.647     1863627.388      599342.901
     1863859.593      599379.793     1864211.156      599403.665
#Sta/Elev= 30
       0  873.45    47.7  858.21    57.3  855.78    66.8  854.11   143.2  844.63
   152.8  843.01   171.8  837.47   181.4   833.7   200.5  824.73   219.6   814.9
   248.2   798.6   286.4  781.83   334.6   756.1     364  741.98   393.4  730.78
   422.8  722.13   432.6  718.53   442.4   715.8   448.6   715.4   481.6   715.2
     511   715.1   628.5  716.79   667.6  718.68   677.4  720.39   687.2   724.1
   716.6  738.92   794.9  773.38   814.4  781.28   873.2  797.85   902.5  804.05
#Mann= 3 , 0 , 0
       0      .1       0   448.6    .045       0   481.6     .05       0
Bank Sta=448.6,481.6
XS Rating Curve= 0 ,0
Exp/Cntr=0.3,0.1

Type RM Length L Ch R = 1 ,10365.4 ,507.1,531.2,554.3
XS GIS Cut Line= 4
     1863299.697      599386.304     1863638.239      599859.394
     1863948.569      599883.265     1864258.899      600184.915
#Sta/Elev= 30
       0  847.88    29.1  842.75    67.9  831.06      97  818.52   145.4  794.29
   155.1  790.84     349  748.11   387.8  741.18   407.2  739.02   581.7  733.69
   630.4  735.07   640.1  734.55   659.6  729.82   701.5  716.18   708.2     715
   737.4  715.37   912.7  720.34   991.4  720.15  1040.5  725.43  1089.7  732.75
  1109.4  734.03  1119.2  737.36  1178.2  768.06  1207.7  782.43  1217.6  785.54
  1227.4  787.14  1276.6  792.44  1286.4  795.23  1306.1  803.43  1325.8  808.56
#Mann= 3 , 0 , 0
       0      .1       0   701.5    .045       0   737.4     .05       0
Bank Sta=701.5,737.4
XS Rating Curve= 0 ,0
Exp/Cntr=0.3,0.1

Type RM Length L Ch R = 1 ,9834.2  ,343.3,350.1,356.7
XS GIS Cut Line= 4
     1863228.083      599405.835     1863484.159      600002.623
     1863668.621      600386.738     1863893.013      600787.201
#Sta/Elev= 30
       0  845.67    49.2  834.33      59  831.35   157.4  791.51   177.1  784.36
   255.8  765.95   354.2  745.05   373.9  741.56   432.9  735.94     492  732.21
   688.2   724.5   833.4  721.46   959.3  714.32   978.7  713.42   988.4  714.66
  1036.8  730.56  1046.5  732.26  1075.5  734.66    1095  738.06  1114.6     744
  1143.9  754.39  1163.4  760.01  1212.3  766.43    1222  768.65  1270.9  784.22
  1309.9  792.98  1329.5  799.04  1388.1  819.97  1485.7  851.61  1534.6   866.5
#Mann= 3 , 0 , 0
       0     .05       0   959.3    .045       0   988.4      .1       0
Bank Sta=959.3,988.4
XS Rating Curve= 0 ,0
Exp/Cntr=0.3,0.1

Type RM Length L Ch R = 1 ,9484.2  ,225.5,232,239.1
XS GIS Cut Line= 4
     1863132.597      599387.895     1863257.597      600110.117
     1863330.513      600592.756     1863410.375      600971.228
#Sta/Elev= 30
       0   845.5    48.9  832.14   136.8  799.08   175.9  786.03   205.2  777.55
   244.3  767.92   283.4  756.07   293.2  753.65     303  752.05   322.5  750.91
   381.1  750.02   488.6  746.12   605.9  735.54   635.2  731.54   664.6  728.87
   986.8  713.61   996.5   713.3  1018.3  713.82  1074.6  717.73  1084.4  719.05
  1103.9  725.09  1113.7  727.45  1133.2  730.84  1259.8  756.11  1288.8  762.84
  1317.8  770.83  1337.1  777.22  1356.5  784.53  1433.8  816.05  1607.9  869.57
#Mann= 3 , 0 , 0
       0     .05       0   986.8    .045       0  1018.3     .06       0
Bank Sta=986.8,1018.3
XS Rating Curve= 0 ,0
Exp/Cntr=0.3,0.1

Type RM Length L Ch R = 1 ,9252.1  ,138.2,158.3,177.2
XS GIS Cut Line= 4
     1863058.595      599396.576     1863093.317      600225.569
     1863054.255      600464.284     1863340.713      601130.517
#Sta/Elev= 30
       0  839.12    29.3  827.81   136.7  776.77   146.4  773.23   156.2  771.51
   302.6  785.72   341.6  787.27     410  787.22   429.5   784.6   507.6     765
   595.4  752.93   624.7  744.54   683.3  730.92   722.3  719.27   771.2  720.19
   955.5  713.64   974.8   713.3   994.2  713.67    1101  721.14  1120.6  724.53
  1257.8  762.43  1316.6  784.74  1375.4  810.47  1404.8  821.33  1453.8  833.61
  1512.6  843.34  1571.4  861.69    1591  863.12  1669.4  855.34  1796.8   831.7
#Mann= 3 , 0 , 0
       0     .05       0   955.5    .045       0   994.2     .06       0
Bank Sta=955.5,994.2
XS Rating Curve= 0 ,0
Exp/Cntr=0.3,0.1

Type RM Length L Ch R = 1 ,9093.8  ,75.6,78,80.3
XS GIS Cut Line= 4
     1862997.831      599674.353     1863047.744      600210.378
     1862871.963      600321.055     1862529.081      601039.371
#Sta/Elev= 30
       0  813.94    48.9  816.34    68.5  814.57    88.1  808.63   146.8  787.17
   195.8  771.52   313.2  746.62   332.8  741.59   362.2  731.75   420.9  718.52
   440.5  717.46   528.6  718.25   613.9  715.83   632.8  713.91   661.1  713.24
   670.5  713.22   775.6  714.08   873.8  717.03   932.8  723.68    1031  725.88
  1080.2  728.75    1149   738.2  1178.4  744.79    1257  769.88  1306.2  792.46
  1325.8  800.12  1365.1  802.13  1453.6  800.67  1492.9   803.3    1542   811.6
#Mann= 3 , 0 , 0
       0     .06       0   632.8    .045       0   661.1     .05       0
Bank Sta=632.8,661.1
XS Rating Curve= 0 ,0
Exp/Cntr=0.3,0.1

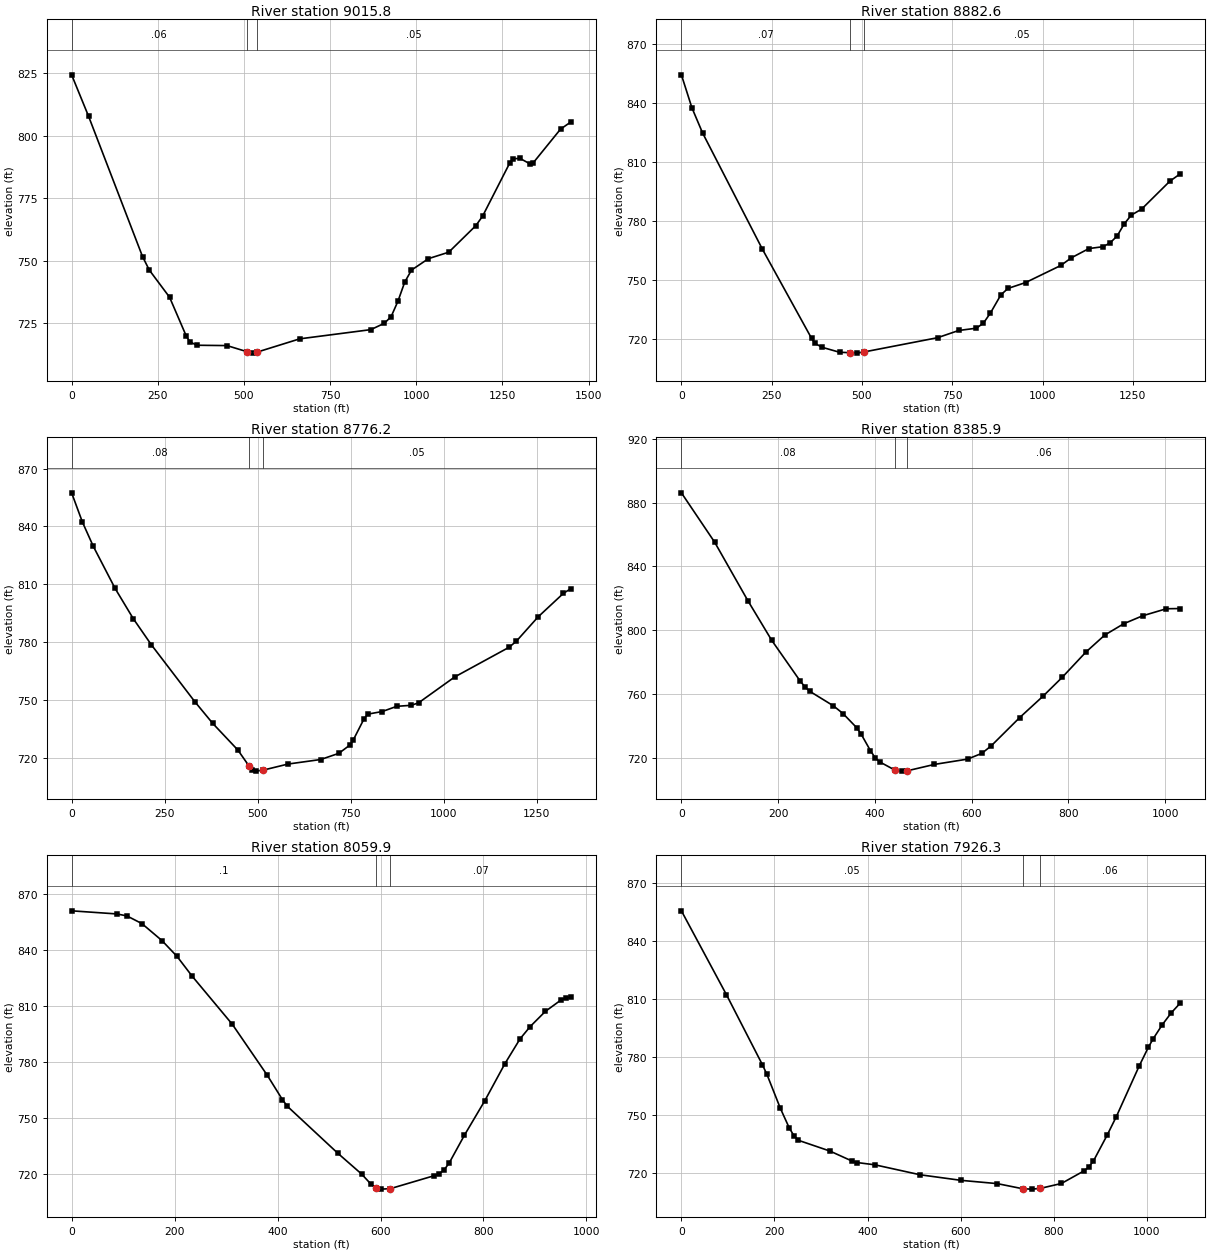
Type RM Length L Ch R = 1 ,9015.8  ,149,133.3,117.6
XS GIS Cut Line= 4
     1862939.237      599713.416     1862997.831      600160.465
     1862843.751      600236.419     1862458.986      600966.888
#Sta/Elev= 30
       0  824.26      49  807.77   205.8  751.63   225.4  746.25   284.2   735.4
   333.2  719.72     343  717.62   362.7   716.2   450.9  716.06   508.1  713.66
   527.2  713.05   539.3   713.5     662  718.76   868.4  722.44   907.7  724.99
   927.3  727.66     947   733.8   966.7  741.43   986.3  746.23  1035.5   750.8
  1094.4  753.38  1173.1     764  1192.7   767.8  1271.4  789.01  1281.2  790.67
  1300.8   790.9  1330.3  788.67  1340.2   789.2  1418.8  802.55  1448.3  805.38
#Mann= 3 , 0 , 0
       0     .06       0   508.1    .045       0   539.3     .05       0
Bank Sta=508.1,539.3
XS Rating Curve= 0 ,0
Exp/Cntr=0.3,0.1

Type RM Length L Ch R = 1 ,8882.6  ,115.2,106.4,97.9
XS GIS Cut Line= 4
     1862857.423      599643.971     1862875.652      600013.763
     1862779.298      600224.701     1862453.777      600933.034
#Sta/Elev= 30
       0  854.37    29.2  837.58    58.5  824.89   224.1  765.82   360.5  720.42
   370.2  717.87   389.6  715.91   437.9  713.39   466.9  713.18   485.5  712.95
   505.5  713.54   709.3  720.79   767.8  724.46   816.5  725.61     836  728.14
   855.5   733.3   884.7  742.61   904.2  745.82   952.9  748.81  1050.4  757.49
  1079.6  761.39  1128.3  766.09  1167.3  767.03  1186.8  768.95  1206.3  772.46
  1225.8  778.57  1245.3  783.04  1274.5  786.19  1352.5  800.35  1381.7  804.14
#Mann= 3 , 0 , 0
       0     .07       0   466.9    .045       0   505.5     .05       0
Bank Sta=466.9,505.5
XS Rating Curve= 0 ,0
Exp/Cntr=0.3,0.1

Type RM Length L Ch R = 1 ,8776.2  ,401.6,390.3,378.4
XS GIS Cut Line= 4
     1862720.053      599633.121     1862733.074      599973.833
     1862726.564      600214.718     1862433.595      600915.673
#Sta/Elev= 30
       0  857.46    29.2  842.19    58.4  829.64   116.9  807.84   165.6   792.2
   214.3   778.6   331.2  749.06   379.5  737.76     447  723.95   475.9  715.94
   485.5  713.81   495.2  713.02   514.5  713.52   581.9   716.7   669.6  719.05
   718.3  722.25   747.5  726.47   757.2  729.21   786.5  740.32   796.2   742.6
   835.2  743.96   874.1  746.66   913.1  747.18   932.6  748.46    1030  761.92
  1176.1  777.31  1195.6  780.46    1254  793.07  1322.2  805.32  1341.6  807.67
#Mann= 3 , 0 , 0
       0     .08       0   475.9    .045       0   514.5     .05       0
Bank Sta=475.9,514.5
XS Rating Curve= 0 ,0
Exp/Cntr=0.3,0.1

Type RM Length L Ch R = 1 ,8385.9  ,331.1,325.9,320.8
XS GIS Cut Line= 4
     1862207.901      599947.791     1862364.151       600242.93
     1862448.786      600412.201     1862394.533      600917.843
#Sta/Elev= 30
       0  886.16    68.8  855.18   137.5  818.48   186.6  793.72   245.6  768.12
   255.4  764.49   265.2  761.73   314.3  752.57     334  747.77   362.3  738.89
   371.8  734.72   390.7  724.54   400.2  720.18   409.6  717.49   441.3  712.29
   456.3  711.64   466.4  711.81   523.2  715.86   591.7  719.18     621  722.77
   640.6  727.53   699.2  745.18   748.1  758.78   787.2  770.44   836.2  786.29
   875.3  796.99   914.4  804.06   953.5  809.05  1002.4  813.46  1031.7   813.6
#Mann= 3 , 0 , 0
       0     .08       0   441.3    .045       0   466.4     .06       0
Bank Sta=441.3,466.4
XS Rating Curve= 0 ,0
Exp/Cntr=0.3,0.1

Type RM Length L Ch R = 1 ,8059.9  ,150.8,133.6,115.8
XS GIS Cut Line= 4
     1862016.928      600006.385     1862142.796      600507.687
     1862240.453      600631.385      1862351.13      600904.822
#Sta/Elev= 30
       0  861.19    87.8  859.52   107.3  858.47   136.5  854.33   175.5   845.2
   204.8  836.69     234  826.12   312.1  800.23   380.3  772.73   409.6  759.69
   419.3   756.1   516.9  730.98   563.2  719.78   581.8  714.23   591.9   712.1
   600.3  711.66   618.8  711.89     704  718.86   713.8  719.88   723.6  722.01
   733.5  725.75     763  740.63   802.3  759.02   841.6  779.05   871.1  792.42
   890.8  799.03   920.3  807.18   949.8  813.12   959.6  814.47   969.4  814.68
#Mann= 3 , 0 , 0
       0      .1       0   591.9    .045       0   618.8     .07       0
Bank Sta=591.9,618.8
XS Rating Curve= 0 ,0
Exp/Cntr=0.3,0.1

Type RM Length L Ch R = 1 ,7926.3  ,83.5,71.6,66.9
XS GIS Cut Line= 5
     1861472.223      600268.971     1861828.126      600535.899
     1862034.289      600646.576     1862171.008      600663.937
     1862309.897       600878.78
#Sta/Elev= 30
       0  855.75    96.7  812.36   174.1  776.04   183.8  771.02   212.8  753.39
   232.1  743.14   241.8  739.32   251.4   736.9   319.2  731.33   367.5  726.06
   377.2  725.39   415.9   724.2   513.1  719.04   600.9  716.16   678.9  714.46
     734  711.78   752.4  711.61   770.8  711.96   816.7  714.54   865.9  721.15
   875.7  723.12   885.6  726.23   915.1  739.64   934.8  749.22     984  775.49
  1003.6  785.11  1013.5  789.34  1033.2  796.68  1052.8  802.94  1072.5  808.09
#Mann= 3 , 0 , 0
       0     .05       0     734    .045       0   770.8     .06       0
Bank Sta=734,770.8
XS Rating Curve= 0 ,0
Exp/Cntr=0.3,0.1

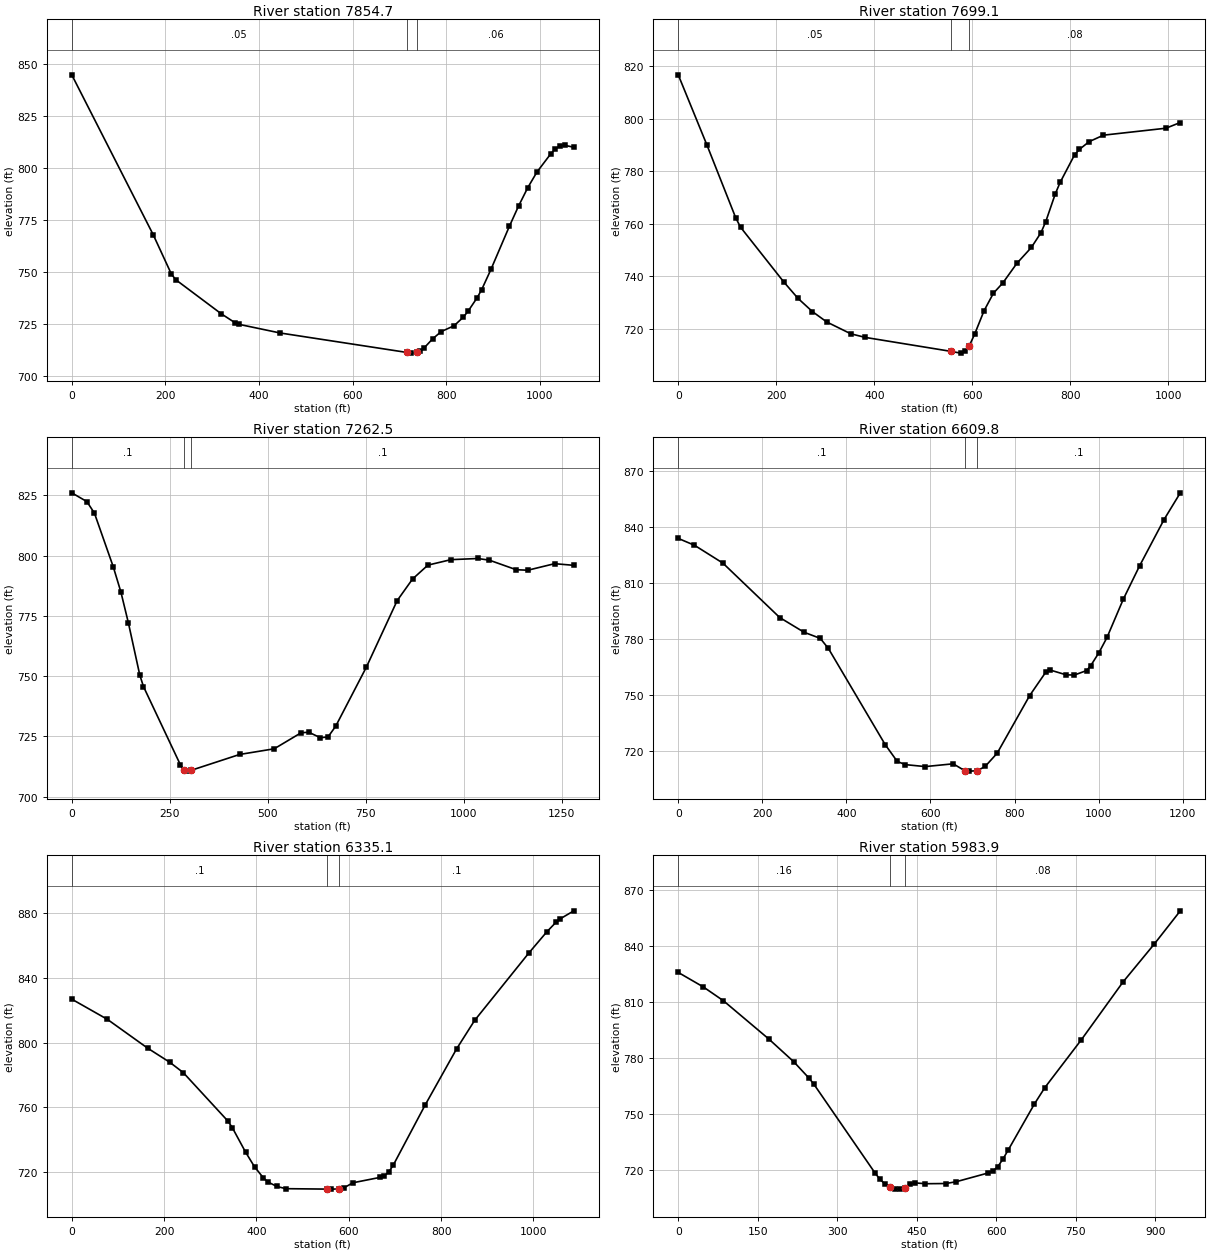
Type RM Length L Ch R = 1 ,7854.7  ,130.7,155.6,173.2
XS GIS Cut Line= 5
     1861459.203      600329.735     1861815.105      600596.662
     1862021.269       600707.34     1862157.987      600724.701
     1862296.876      600939.544
#Sta/Elev= 30
       0  844.76   174.1  767.84   212.8  748.97   222.4  746.22   319.2  729.91
   348.2  725.67   357.8  724.79   444.9  720.67   715.6  711.32   724.8  710.98
   737.4  711.32   743.2  711.79   752.4  713.41   770.8  717.84   789.1  721.32
   816.7  724.15   836.4  728.27   846.2  731.01   865.9  737.59   875.7  741.54
   895.4  751.22   934.8  771.96   954.4  781.69   974.1  790.54   993.8  798.07
  1023.3  806.82  1033.2  809.19    1043  810.66  1052.8   810.9  1072.5  809.94
#Mann= 3 , 0 , 0
       0     .05       0   715.6    .045       0   737.4     .06       0
Bank Sta=715.6,737.4
XS Rating Curve= 0 ,0
Exp/Cntr=0.3,0.1

Type RM Length L Ch R = 1 ,7699.1  ,439.5,436.6,433.5
XS GIS Cut Line= 4
      1861413.63      600494.666      1861884.55      600733.381
     1862006.078      600841.888     1862273.005      601041.541
#Sta/Elev= 30
       0  816.74    58.7  789.91   117.3  762.23   127.1  758.66   215.1  737.84
   244.4  731.52   273.8  726.49   303.1  722.53     352  718.04   381.3  716.67
   556.7  711.33   575.9  710.67   585.5  711.36   593.9  713.54   604.6  717.87
   623.8   726.8     643  733.52   662.1   737.4   690.9  744.92   720.3  750.93
   739.9  756.55   749.7  760.78   769.3  771.45   779.1  775.76   808.5  786.24
   818.3  788.31     838  791.25   867.4  793.74   994.8  796.39  1024.2  798.57
#Mann= 3 , 0 , 0
       0     .05       0   556.7    .045       0   593.9     .08       0
Bank Sta=556.7,593.9
XS Rating Curve= 0 ,0
Exp/Cntr=0.3,0.1

Type RM Length L Ch R = 1 ,7262.5  ,645.9,652.7,659.3
XS GIS Cut Line= 4
     1861287.762      600757.253     1861502.605       600865.76
     1861595.921      600922.183     1862370.444      601438.242
#Sta/Elev= 30
       0  826.09    38.5  822.45    57.8  817.65   105.9  795.34   125.2  784.96
   144.4   772.1   173.3  750.55   182.9  745.65     277   713.2   286.1  711.06
   295.2  710.57   304.3   710.9   428.1  717.49   516.3  719.84   584.9   726.5
   604.5  726.71   633.8  724.45   653.4  724.74     673  729.19   751.4  753.77
   829.8  781.34     869   790.3   908.2  796.08   966.9  798.35  1035.5  798.83
  1064.9  798.14  1133.5  794.17  1162.9  793.96  1231.4  796.68  1280.4  795.99
#Mann= 3 , 0 , 0
       0      .1       0   286.1    .045       0   304.3      .1       0
Bank Sta=286.1,304.3
XS Rating Curve= 0 ,0
Exp/Cntr=0.3,0.1

Type RM Length L Ch R = 1 ,6609.8  ,256.7,274.8,292.4
XS GIS Cut Line= 4
     1861146.486      600956.471     1861422.527      601375.742
     1861593.751      601566.715     1861875.869      601898.746
#Sta/Elev= 30
       0  833.78    38.6  830.12   106.2  820.59   241.3  791.54   299.3  783.66
   337.9  780.38   357.2  774.99   492.3  723.64     521  714.67     540  712.98
   587.5  711.92     654  713.41   682.5   709.6     692   709.5     711  709.68
     730     712   758.5  719.04   835.9  749.85   874.7  762.52   884.3  763.51
   923.1   760.9   942.4  760.83   971.5  763.22   981.2  765.87  1000.5  772.69
  1019.9  780.91  1058.6  801.32  1097.4  819.15  1155.4   843.8  1194.2  858.12
#Mann= 3 , 0 , 0
       0      .1       0   682.5    .045       0     711      .1       0
Bank Sta=682.5,711
XS Rating Curve= 0 ,0
Exp/Cntr=0.3,0.1

Type RM Length L Ch R = 1 ,6335.1  ,352,351.1,350.2
XS GIS Cut Line= 4
     1861107.423      601034.596     1861300.131      601391.367
     1861289.715      601594.492     1861245.444      602071.055
#Sta/Elev= 30
       0  826.76    77.2  814.28   164.1  796.56   212.4  787.78   241.4  781.45
   337.9   751.6   347.6  747.52   376.5  732.32   395.8   723.3   415.2  716.39
   424.9  713.91   444.2  711.15   463.6  709.78   553.8  709.51   560.5   709.5
   579.8  709.61   589.5  710.29   608.9  713.42   667.5  716.73   677.3  717.76
     687  720.22   696.8  724.54   765.2   761.3   833.5  796.05   872.6  813.64
   989.8  855.17  1028.9   868.3  1048.4   874.1  1058.2  876.39  1087.5  881.28
#Mann= 3 , 0 , 0
       0      .1       0   553.8    .045       0   579.8      .1       0
Bank Sta=553.8,579.8
XS Rating Curve= 0 ,0
Exp/Cntr=0.3,0.1

Type RM Length L Ch R = 1 ,5983.9  ,231.9,239.1,246.2
XS GIS Cut Line= 4
     1861044.489      601037.201     1861011.937      601291.107
     1861003.256      601529.822     1861027.128      601981.211
#Sta/Elev= 30
       0  825.88    47.4  818.07    85.3  810.65   170.7  790.15   218.1  777.84
   246.5  769.15     256  765.77   370.6  718.39   380.2  714.81   389.8  712.29
   399.3  710.44   408.9   709.5   418.4  709.56     428  710.29   437.5  712.14
   447.1  712.84   466.2   712.4   504.7  712.51   524.3  713.48   583.3  718.08
   593.1  719.13     603  721.65   612.8  725.86   622.6  730.64   671.7  755.21
   691.4  764.02   760.2  789.69   838.8  820.73   897.7  841.08   946.9  858.96
#Mann= 3 , 0 , 0
       0     .16       0   399.3    .045       0     428     .08       0
Bank Sta=399.3,428
XS Rating Curve= 0 ,0
Exp/Cntr=0.3,0.1

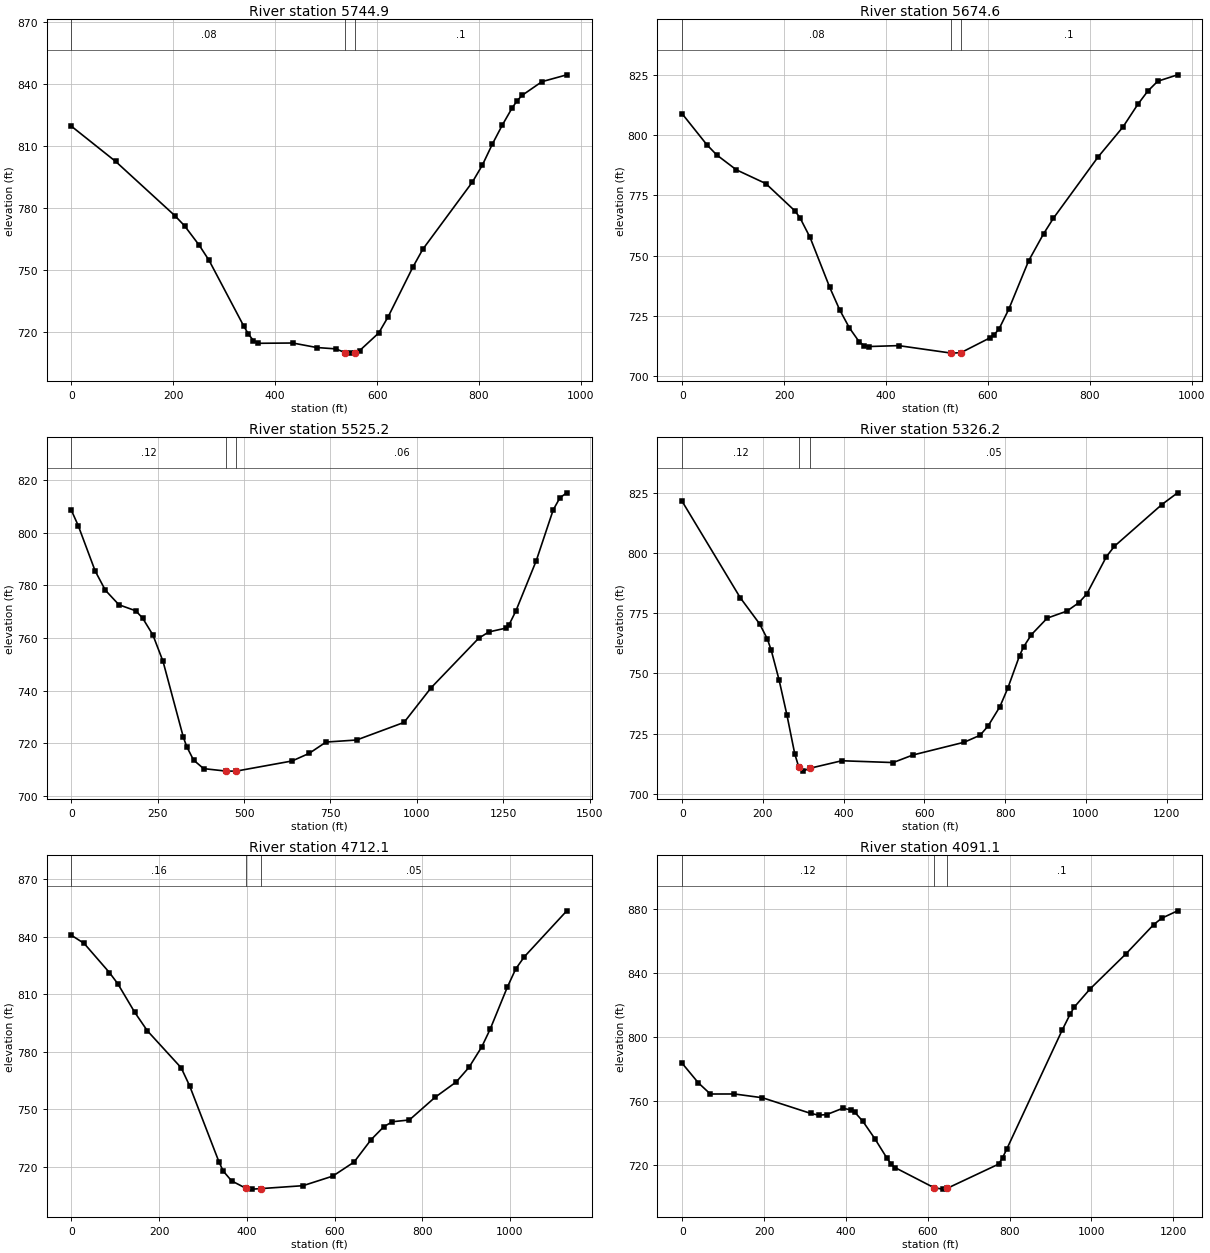
Type RM Length L Ch R = 1 ,5744.9  ,70.5,70.2,70
XS GIS Cut Line= 4
      1860953.56       601032.86     1860852.215      601465.152
     1860791.451      601642.235      1860792.97      601983.381
#Sta/Elev= 30
       0  819.58    86.9  802.48   202.7  776.28     222   771.3     251   761.8
   270.3  754.45   337.8  722.84   347.5  718.72   357.1  715.63   366.8  714.28
   434.4  714.42   481.5  712.23   518.9  711.57   537.6  709.74     547  709.51
   556.3  709.65   565.7  710.72   603.2  719.27   621.9  727.23   670.2  751.22
   689.7  759.89   787.2  792.55   806.7  800.74   826.2  810.88   845.7   820.1
   865.2  828.49   874.9  831.95   884.7  834.58   923.6  841.21   972.4  844.53
#Mann= 3 , 0 , 0
       0     .08       0   537.6    .045       0   556.3      .1       0
Bank Sta=537.6,556.3
XS Rating Curve= 0 ,0
Exp/Cntr=0.3,0.1

Type RM Length L Ch R = 1 ,5674.6  ,132.9,149.5,165.3
XS GIS Cut Line= 4
     1860889.324      601012.027     1860787.979      601444.319
     1860727.215      601621.402     1860728.734      601962.548
#Sta/Elev= 30
       0  808.79    48.3     796    67.6  791.77   106.2  785.58   164.1  779.86
     222  768.37   231.7  765.44     251   757.5   289.6  736.77   308.9  727.55
   328.2  719.96   347.5  714.18   357.1  712.65   366.8  712.24   424.7  712.62
   528.3   709.5     547  709.68   603.2  715.74   612.5  717.18   621.9  719.53
     641   727.7     680   747.8   709.2  758.97   728.7   765.5   816.4  790.92
   865.2  803.35   894.4  812.76   913.9  818.23   933.4  822.33   972.4  824.99
#Mann= 3 , 0 , 0
       0     .08       0   528.3    .045       0     547      .1       0
Bank Sta=528.3,547
XS Rating Curve= 0 ,0
Exp/Cntr=0.3,0.1

Type RM Length L Ch R = 1 ,5525.2  ,212.3,199,186.4
XS GIS Cut Line= 4
     1860853.517      600987.287     1860784.072      601354.041
      1860595.27      601460.378       1860280.6      602243.798
#Sta/Elev= 30
       0  808.44    19.6   802.7    68.8  785.43    98.2  778.16   137.5  772.64
   186.6  770.33   206.3  767.53   235.8   761.2   265.2  751.14   324.2  722.28
     334  718.74   353.6   713.7   382.7  710.45   448.6   709.5   476.9   709.5
     639  713.36   688.1  716.23   737.2  720.53   825.6  721.31     963  727.99
  1041.5  741.16    1179  759.92  1208.4  762.32  1257.5  763.76  1267.3   765.1
    1287  770.36  1345.9   789.4  1394.9  808.66  1414.6  813.29  1434.2  815.12
#Mann= 3 , 0 , 0
       0     .12       0   448.6    .045       0   476.9     .06       0
Bank Sta=448.6,476.9
XS Rating Curve= 0 ,0
Exp/Cntr=0.3,0.1

Type RM Length L Ch R = 1 ,5326.2  ,605.1,614.1,622.1
XS GIS Cut Line= 4
     1860727.649      600963.416     1860645.184       601178.26
     1860575.739      601317.149     1860208.986      602074.527
#Sta/Elev= 30
       0  821.45   143.8  781.45   191.8  770.58     211  764.27   220.5   759.6
   239.8  747.38   259.2  732.85   278.6  716.68   288.4  711.23   298.1  709.42
   317.5  710.66   395.2  713.73   522.4  712.98   571.3  716.12   698.5  721.43
   737.7  724.33   757.2  728.08   786.6  736.13   806.2  743.81   835.5  757.41
   845.3  760.98   864.9  766.13     904  772.99   952.9  775.92   982.3  779.39
  1001.9     783  1050.8  798.58  1070.4  802.84  1187.8  820.16  1226.9  825.05
#Mann= 3 , 0 , 0
       0     .12       0   288.4    .045       0   317.5     .05       0
Bank Sta=288.4,317.5
XS Rating Curve= 0 ,0
Exp/Cntr=0.3,0.1

Type RM Length L Ch R = 1 ,4712.1  ,618.1,621,623.3
XS GIS Cut Line= 4
     1860328.343      600768.103     1860130.861      600991.628
     1859996.312      601113.155     1859562.284      601597.096
#Sta/Elev= 30
       0  840.73    28.9   836.5    86.6  821.28   105.8   815.4   144.3  800.54
   173.2  790.86   250.2  771.58   269.4  762.23   336.4  722.48     346  717.71
   365.1  712.56   398.2  708.63   412.8  708.23   431.9   708.5   528.1  710.03
     596  715.03   644.5  722.36   683.3  734.05   712.4  740.82   731.8  743.41
   770.6  744.33   828.9   756.1   877.4  764.16   906.5  771.78   935.6  782.44
     955  791.79   993.8  813.55  1013.2  823.18  1032.6  829.47  1129.6   853.5
#Mann= 3 , 0 , 0
       0     .16       0   398.2    .045       0   431.9     .05       0
Bank Sta=398.2,431.9
XS Rating Curve= 0 ,0
Exp/Cntr=0.3,0.1

Type RM Length L Ch R = 1 ,4091.1  ,639.3,619.6,599.7
XS GIS Cut Line= 4
     1860111.329       600253.78     1859748.916      600598.833
     1859583.986       600720.36     1859260.635      601108.815
#Sta/Elev= 30
       0  783.66    39.2  771.57    68.7  764.54   127.6  764.56   196.2   762.2
     314  752.44   333.6  751.33   353.2   751.7   392.5  755.66   412.1  754.61
   421.9  753.12   441.5   747.5     471  736.56   500.4  724.49   510.2  720.97
   519.9  718.65   615.9     706     637  705.17   646.7  705.57   773.3  720.78
     783  724.78   792.8  729.95   928.8   804.5   948.3  814.48     958  818.75
   996.9  830.14  1084.3  851.97  1152.4   870.3  1171.8  874.25  1210.7  878.88
#Mann= 3 , 0 , 0
       0     .12       0   615.9    .045       0   646.7      .1       0
Bank Sta=615.9,646.7
XS Rating Curve= 0 ,0
Exp/Cntr=0.3,0.1

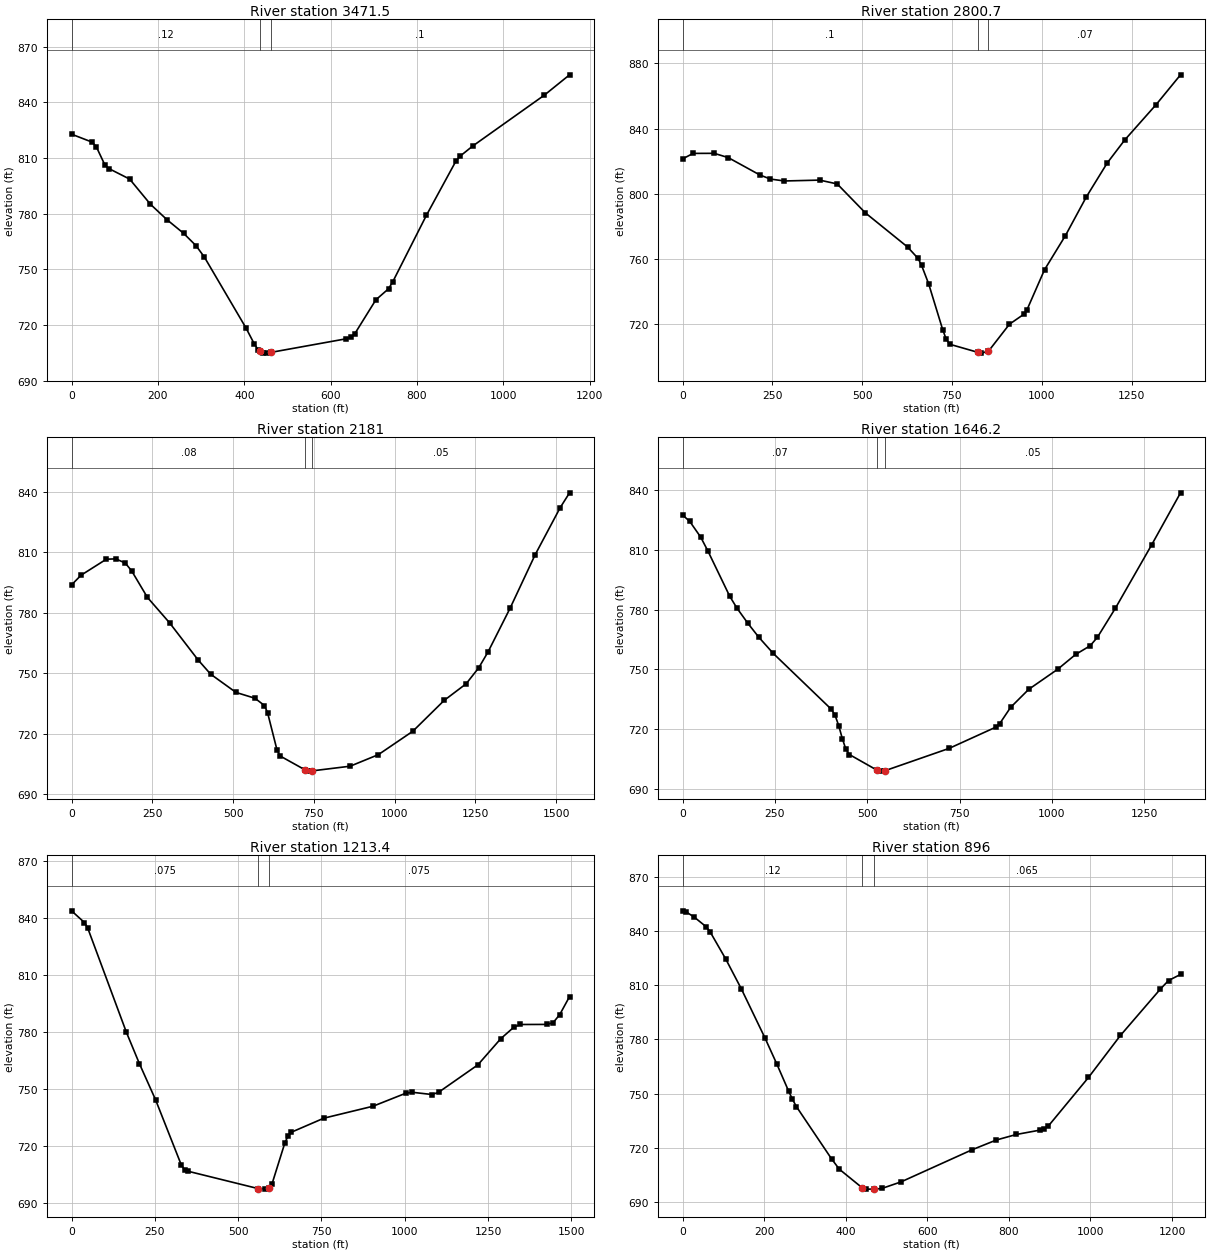
Type RM Length L Ch R = 1 ,3471.5  ,681,670.8,660.2
XS GIS Cut Line= 4
     1859215.062      599921.749     1859143.447      600299.353
     1859130.427      600453.433     1859143.447      601067.583
#Sta/Elev= 30
       0  822.79      48  818.48    57.6  815.88    76.9  806.35    86.5  804.27
   134.5  798.62   182.6  785.08     221  776.74   259.4  769.43   288.2  762.77
   307.5  756.65   403.7  718.56     423  709.94   432.7  706.44   436.9   705.8
   442.3  704.98   451.9  704.92   461.6  705.32   636.5  712.66   646.2  713.39
     656   715.4   704.7  733.63     734  739.56   743.7  743.28   821.7   779.1
     890  808.28   899.7  810.96     929  816.42  1094.8   843.8  1153.2  854.75
#Mann= 3 , 0 , 0
       0     .12       0   436.9    .045       0   461.6      .1       0
Bank Sta=436.9,461.6
XS Rating Curve= 0 ,0
Exp/Cntr=0.3,0.1

Type RM Length L Ch R = 1 ,2800.7  ,614.5,619.7,622.8
XS GIS Cut Line= 4
     1858698.135      599917.409     1858573.135       600591.02
     1858677.302      600854.909     1858892.579      601212.548
#Sta/Elev= 30
       0   821.4    29.4   824.8    88.1  824.84   127.2  822.22   215.3  811.55
   244.7  809.04   283.8  807.87   381.7   808.4   430.6  806.05   508.9   788.3
   626.4  767.34   655.8  760.28   665.5     756   685.1  744.75   724.2  716.59
     734  710.72   743.8  707.64   822.1  702.68   831.8  702.19   851.4   703.3
   910.1  719.97   949.2  725.91     959  728.88  1007.6  753.36  1065.9  774.36
  1124.1  798.11  1182.4  818.99  1230.9  833.03  1318.3  854.75  1386.2  873.03
#Mann= 3 , 0 , 0
       0      .1       0   822.1    .045       0   851.4     .07       0
Bank Sta=822.1,851.4
XS Rating Curve= 0 ,0
Exp/Cntr=0.3,0.1

Type RM Length L Ch R = 1 ,2181    ,528.9,534.9,540.5
XS GIS Cut Line= 4
      1857941.19      600052.826      1858034.94      600682.166
     1858081.815       600903.52     1858266.711      601557.166
#Sta/Elev= 30
       0  793.89    29.4  798.68   107.7  806.63     137   806.8   166.4   804.7
     186  800.84   234.9  787.64   303.5  775.01   391.6  756.61   430.7   749.5
     509  740.45   567.8  737.55   597.1  733.94   606.9  730.34   636.3  711.71
   646.1  708.83   723.1  701.95   734.7  701.34   744.5  701.46   862.6  703.79
   949.9  709.53  1056.6  721.16  1153.7  736.49  1221.6  744.73  1260.4  752.62
  1289.5  760.58  1357.5  782.22  1435.1  808.79  1512.7  832.22  1541.8  839.61
#Mann= 3 , 0 , 0
       0     .08       0   723.1    .045       0   744.5     .05       0
Bank Sta=723.1,744.5
XS Rating Curve= 0 ,0
Exp/Cntr=0.3,0.1

Type RM Length L Ch R = 1 ,1646.2  ,430.7,432.8,433.9
XS GIS Cut Line= 4
     1857685.982       600372.27     1857699.003      600804.562
     1857688.586      601054.562      1857646.92      601718.624
#Sta/Elev= 30
       0  827.57    19.7  824.28    49.2  816.41    68.8   809.4   127.8  786.68
   147.4  780.71   176.9   773.1   206.4  766.11   245.7  757.95     403  729.85
   412.8  726.91   422.7  721.72   432.5  715.19   442.1  709.81   451.7  707.13
   527.3  699.18   538.4  698.79     548     699   721.8  710.23     849  720.97
   858.8  722.72   888.2  730.85   937.1  739.89  1015.4  749.98  1064.3  757.46
  1103.4   761.8    1123  766.03    1172  780.75  1269.8  812.48  1348.1  838.69
#Mann= 3 , 0 , 0
       0     .07       0   527.3    .045       0     548     .05       0
Bank Sta=527.3,548
XS Rating Curve= 0 ,0
Exp/Cntr=0.3,0.1

Type RM Length L Ch R = 1 ,1213.4  ,311.4,317.4,323.8
XS GIS Cut Line= 4
     1857399.524      600438.242     1857343.968      600851.437
     1857302.302      601139.631     1857212.024      601920.881
#Sta/Elev= 30
       0  843.88    38.8  837.68    48.5   834.8   164.8  779.76   203.6  763.33
   252.1   744.3   329.6  709.82   339.4  707.41     349  706.65   559.6   697.5
   581.9   697.2   591.6  697.59   601.3  699.77   640.2  721.59   649.9  725.32
   659.6  727.19   757.3   734.6   904.7  740.89    1003  747.74  1022.7  748.24
  1081.7  747.06  1101.3  748.21  1219.3  762.68  1288.1  776.48  1327.4  782.54
  1347.1  783.97  1425.7  784.01  1445.4  784.95  1465.1  789.18  1494.6  798.68
#Mann= 3 , 0 , 0
       0    .075       0   559.6    .045       0   591.6    .075       0
Bank Sta=559.6,591.6
XS Rating Curve= 0 ,0
Exp/Cntr=0.3,0.1

Type RM Length L Ch R = 1 ,896     ,367.2,375.3,382.2
XS GIS Cut Line= 4
     1857297.961      600400.916     1857139.107      600719.492
      1857053.17      600929.562     1856813.586      601520.708
#Sta/Elev= 30
       0  851.14     9.6  850.43    28.9  847.63    57.7  842.37    67.4   839.6
   105.8  824.53   144.3  807.91     202  780.87   230.9  766.53   259.8  751.56
   269.4   746.9     279   742.9   365.4  713.92   384.4  708.21   441.1  697.82
   450.6   697.2   469.5   697.2   488.4  697.55   535.7  701.21   710.5  719.04
   769.4  724.38   818.5  727.44   877.4  729.89   887.2  730.64     897  732.16
   995.1  758.95  1073.6  782.24  1171.7  807.93  1191.4  812.59  1220.8  815.95
#Mann= 3 , 0 , 0
       0     .12       0   441.1    .045       0   469.5    .065       0
Bank Sta=441.1,469.5
XS Rating Curve= 0 ,0
Exp/Cntr=0.3,0.1

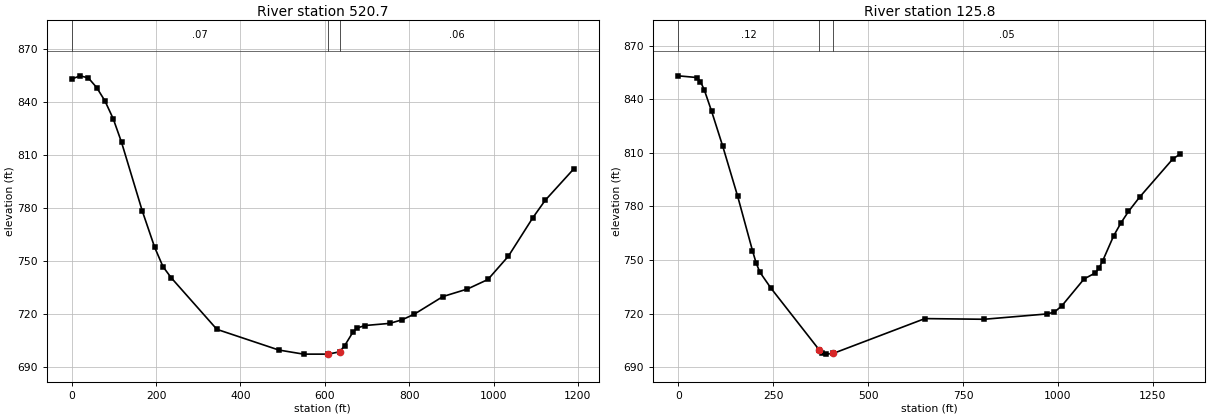
Type RM Length L Ch R = 1 ,520.7   ,394.5,394.9,395.8
XS GIS Cut Line= 4
      1857128.69       600403.52     1856870.878      600762.895
     1856683.378      600986.853     1856420.357      601359.249
#Sta/Elev= 30
       0  852.76    19.7  854.57    39.3  853.38      59  847.96    78.6  840.41
    98.3  830.27   117.9  817.06   167.1   778.2   196.6  757.55   216.2  746.68
   235.9  740.34     344  711.22     491  699.51   549.4   697.2   607.8   697.2
   634.8   698.5   646.8  701.93   666.2  709.49     676  711.94   695.4  713.38
   753.8  714.59   782.9   716.6     812  719.78   879.9  729.76   938.1  734.03
   986.6  739.41  1035.1  752.58  1093.3  774.41  1122.4  784.18  1190.3     802
#Mann= 3 , 0 , 0
       0     .07       0   607.8    .045       0   634.8     .06       0
Bank Sta=607.8,634.8
XS Rating Curve= 0 ,0
Exp/Cntr=0.3,0.1

Type RM Length L Ch R = 1 ,125.8   ,126.1,125.8,125.5
XS GIS Cut Line= 4
      1857034.94       600341.02      1856803.17      600445.187
     1856592.232      600669.145     1856217.232      601330.603
#Sta/Elev= 30
       0  853.12    48.9  852.17    58.6  849.81    68.4  845.38      88  833.19
   117.3  813.61   156.4  785.73   195.5  755.24   205.2  748.27     215  743.16
   244.3  734.16   370.6  699.82   379.1  697.86   388.7  697.27   407.9  697.65
   649.5  717.17   805.5  716.79   971.2  719.78   990.7  720.82  1010.2  724.33
  1068.7  739.38  1097.9   742.7  1107.7  745.33  1117.4  749.36  1146.6  763.53
  1166.2   770.9  1185.6  777.15  1214.9  785.18  1302.6  806.63  1322.1  809.34
#Mann= 3 , 0 , 0
       0     .12       0   370.6    .045       0   407.9     .05       0
Bank Sta=370.6,407.9
XS Rating Curve= 0 ,0
Exp/Cntr=0.3,0.1

Chan Stop Cuts=-1
Use User Specified Reach Order=0
Composite Channel Slope=5